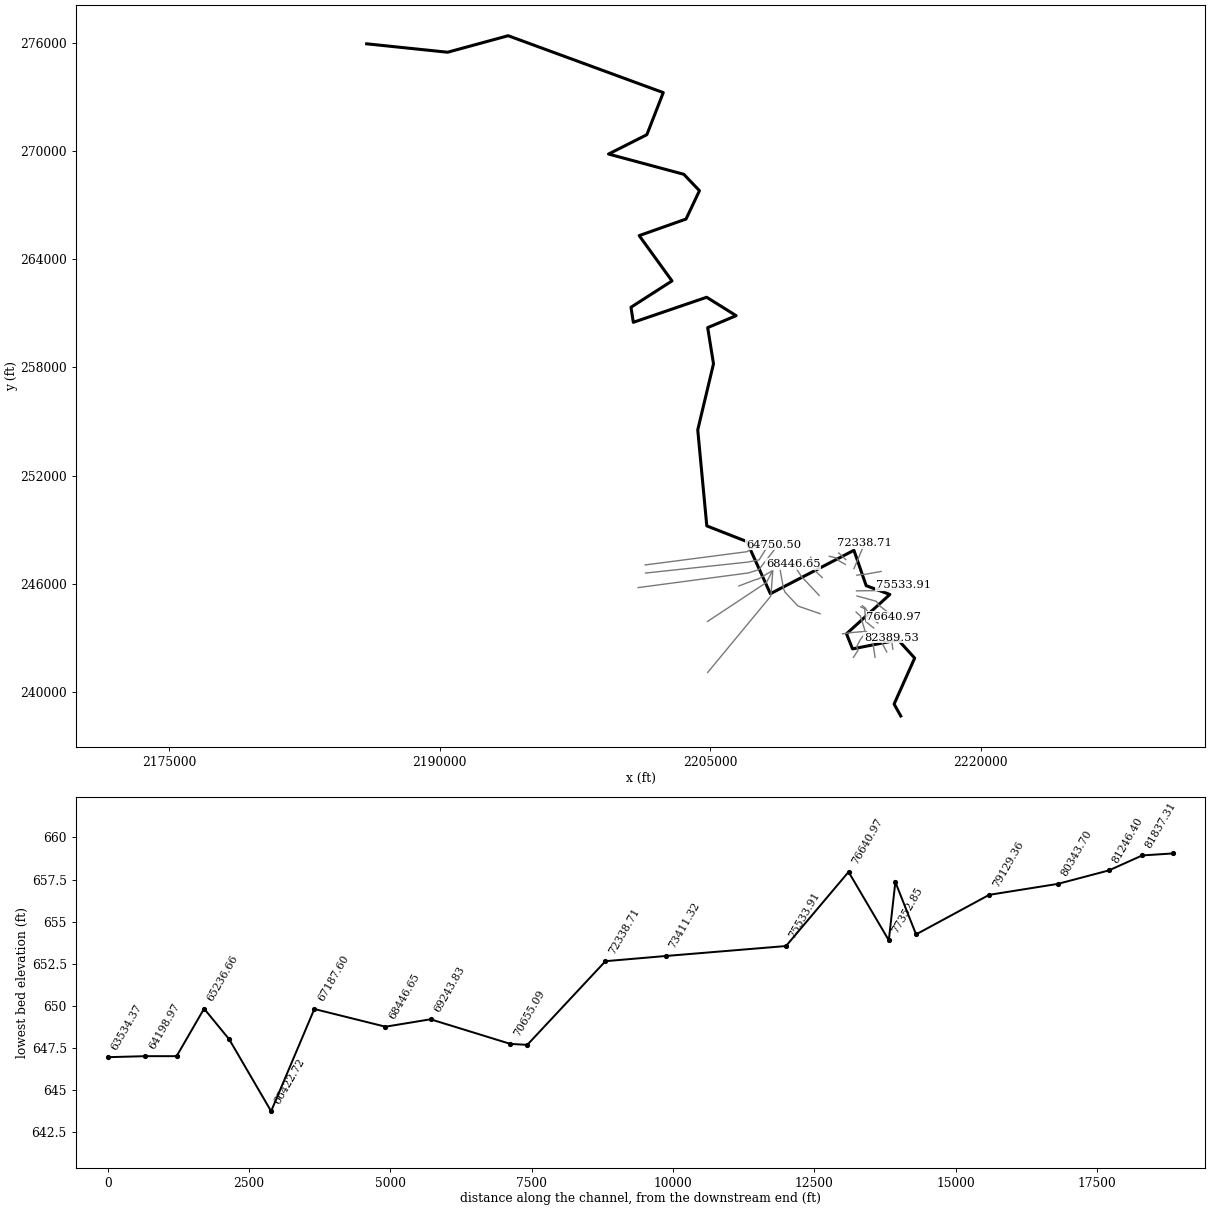
--- SouthChickamauga.prj (project) ---

Proj Title=South Chickamauga
Current Plan=p12
Default Exp/Contr=0.3,0.1
English Units
Geom File=g06
Geom File=g09
Geom File=g10
Geom File=g12
Flow File=f03
Flow File=f04
Plan File=p07
Plan File=p09
Plan File=p10
Plan File=p12
Y Axis Title=Elevation
X Axis Title(PF)=Main Channel Distance
X Axis Title(XS)=Station
BEGIN DESCRIPTION:
END DESCRIPTION:
DSS File=dss
DSS Export Rating Curves= 0
DSS Export Rating Curve Sorted= 0
DSS Export Volume Flow Curves= 0
DXF Filename=..\..\..\..\HEC-RAS\South Chickamauga\South Chickamauga Creek_HEC-RAS 5.0.3\SouthChickamauga.
DXF OffsetX= 0
DXF OffsetY= 0
DXF ScaleX= 1
DXF ScaleY= 10
Specific Locations Profile Table=SChickamauga FIS Locations           , 7
Chickamauga     ,1               ,63534.37
Chickamauga     ,1               ,64750.50
Chickamauga     ,1               ,65236.66
Chickamauga     ,1               ,70655.09
Chickamauga     ,1               ,72338.71
Chickamauga     ,1               ,77468.57
Chickamauga     ,1               ,82389.53

--- SouthChickamauga.p12 (plan) ---

Plan Title=Natural Conditions
Program Version=5.03
Short Identifier=NC
Geom File=g12
Flow File=f04
Subcritical Flow
K Sum by GR= 0
Std Step Tol= 0.01
Critical Tol= 0.01
Num of Std Step Trials= 20
Max Error Tol= 0.3
Flow Tol Ratio= 0.001
Split Flow NTrial= 30
Split Flow Tol= 0.02
Split Flow Ratio= 0.02
Log Output Level= 0
Friction Slope Method= 1
Unsteady Friction Slope Method= 2
Unsteady Bridges Friction Slope Method= 1
Parabolic Critical Depth
Global Vel Dist= 0 , 0 , 0
Global Log Level= 0
CheckData=True
Encroach Param=-1 ,0,0, 0
BEGIN DESCRIPTION:
South Chickamauga Creek
Natural Conditions Model
I-75 at River Station 65026 removed from model
Cross Section Geometry:  From Effective FIS Model and Field Survey
Discharges:  From Effective FIS Model
END DESCRIPTION:
Computation Interval=1MIN
Output Interval=1HOUR
Instantaneous Interval=1HOUR
Mapping Interval=1HOUR
Run HTab= 0
Run UNet= 0
Run Sediment= 0
Run PostProcess= 0
Run WQNet= 0
Run RASMapper= 0
UNET Theta= 1
UNET Theta Warmup= 1
UNET ZTol= 0.02
UNET ZSATol= 0.02
UNET MxIter= 20
UNET Max Iter WO Improvement= 0
UNET MaxInSteps= 0
UNET DtIC= 0
UNET DtMin= 0
UNET MaxCRTS= 20
UNET WFStab= 2
UNET SFStab= 1
UNET WFX= 1
UNET SFX= 1
UNET DSS MLevel= 4
UNET Pardiso=0
UNET DZMax Abort= 100
UNET Use Existing IB Tables=-1
UNET Froude Reduction=False
UNET Froude Limit= 0.8
UNET Froude Power= 4
UNET Time Slicing=0,0, 5
UNET D1 Cores= 0
UNET D2 Coriolis=0
UNET D2 Cores= 0
UNET D2 Theta= 1
UNET D2 Theta Warmup= 1
UNET D2 Z Tol= 0.01
UNET D2 Volume Tol= 0.01
UNET D2 Max Iterations= 20
UNET D2 Equation= 0
UNET D2 RampUpFraction=0.1
UNET D2 TimeSlices= 1
UNET D2 BCVolumeCheck=0
UNET D1D2 MaxIter= 0
UNET D1D2 ZTol=0.01
UNET D1D2 QTol=0.1
UNET D1D2 MinQTol=1
Write IC File= 0
Write IC File at Fixed DateTime=0
Write IC File at Sim End=0
Echo Input=False
Echo Parameters=False
Echo Output=False
Write Detailed= 0
HDF Write Warmup=0
HDF Write Time Slices=0
HDF Flush=0
HDF Face Node Velocities=0
HDF Compression= 1
HDF Chunk Size= 1
HDF Spatial Parts= 1
HDF Use Max Rows=0
HDF Fixed Rows= 1
Calibration Method= 0
Calibration Iterations= 20
Calibration Max Change=0.05
Calibration Tolerance=0.2
Calibration Maximum=1.5
Calibration Minimum=0.5
Calibration Optimization Method= 1
WQ AD Non Conservative
WQ ULTIMATE=-1
WQ Max Comp Step=1HOUR
WQ Output Interval=15MIN
WQ Output Selected Increments= 0
WQ Output face flow=0
WQ Output face velocity=0
WQ Output face area=0
WQ Output face dispersion=0
WQ Output cell volume=0
WQ Output cell surface area=0
WQ Output cell continuity=0
WQ Output cumulative cell continuity=0
WQ Output face conc=0
WQ Output face dconc_dx=0
WQ Output face courant=0
WQ Output face peclet=0
WQ Output face adv mass=0
WQ Output face disp mass=0
WQ Output cell mass=0
WQ Output cell source sink temp=0
WQ Output nsm pathways=0
WQ Output nsm derived pathways=0
WQ Output MaxMinRange=-1
WQ Daily Max Min Mean=-1
WQ Daily Range=0
WQ Daily Time=0
WQ Create Restart=0
WQ Fixed Restart=0
WQ System Summary=0
WQ Write To DSS=0
WQ Use Fixed Temperature=0
Sorting and Armoring Iterations= 10
XS Update Threshold= 0.02
Bed Roughness Predictor= 0
Hydraulics Update Threshold= 0.02
Energy Slope Method= 1
Volume Change Method= 1
Sediment Retention Method= 0
XS Weighting Method= 0
Number of US Weighted Cross Sections= 1
Number of DS Weighted Cross Sections= 1
Upstream XS Weight=0
Main XS Weight=1
Downstream XS Weight=0
Number of DS XS's Weighted with US Boundary= 1
Upstream Boundary Weight= 1
Weight of XSs Associated with US Boundary= 0
Number of US XS's Weighted with DS Boundary= 1
Downstream Boundary Weight= 0.5
Weight of XSs Associated with DS Boundary= 0.5
Percentile Method= 0
Sediment Output Level= 4
Mass or Volume Output= 0
Output Increment Type= 1
Profile and TS Output Increment= 1
XS Output Flag= 0
XS Output Increment= 10
Write Gradation File= 0
Read Gradation Hotstart= 0
Write HDF5 File= 1
Write DSS Sediment File= 0
SV Curve= 0
Specific Gage Flag= 0

--- SouthChickamauga.p07 (plan) ---

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Plan Title=Duplicate Effective
Short Identifier=Duplicate 5.0.3
Geom File=g06
Flow File=f03
Duplicate Effective Model
I-75 at River Station 65026
Cross Section Geometry:  From Effective FIS Model
Computation Interval=1HOUR
UNET ZSATol= 0.05
UNET Froude Limit= 1
UNET Froude Power= 10
Volume Change Method= 0
Upstream XS Weight=0.25
Main XS Weight=0.5
Downstream XS Weight=0.25
Profile and TS Output Increment= 10

--- SouthChickamauga.p09 (plan) ---

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Plan Title=Existing
Short Identifier=Existing
Geom File=g09
Flow File=f04
Existing Conditions Model
Bridge Data:
 - I-75 at River Station 65026
 - Modeled using internal bridge sections
 - Bridge and internal section geometry from survey

--- SouthChickamauga.p10 (plan) ---

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Plan Title=Proposed
Short Identifier=Proposed
Geom File=g10
Flow File=f04
Proposed Conditions Model
Bridge Data:
 - I-75 at River Station 65026
 - Modeled using internal bridge sections
 - Bridge and internal section geometry from  Preliminary Plans
DSS File=dss

--- SouthChickamauga.f04 (steady flow) ---

Flow Title=Existing
Program Version=5.03
Number of Profiles= 4
Profile Names=10-yr,50-yr,100-yr,500-yr
River Rch & RM=Chickamauga,1               ,82389.53
   18070   25240   28620   36620
River Rch & RM=Chickamauga,1               ,77468.57
   18140   25460   28730   36730
River Rch & RM=Chickamauga,1               ,72338.71
   18200   25680   28840   36840
River Rch & RM=Chickamauga,1               ,70655.09
   18230   25750   28870   36870
River Rch & RM=Chickamauga,1               ,66422.72
   18300   26000   29000   37000
River Rch & RM=Chickamauga,1               ,65236.66
   22400   29500   32600   44000
River Rch & RM=Chickamauga,1               ,64750.50
   22410   29510   32610   44010
River Rch & RM=Chickamauga,1               ,63534.37
   22420   29520   32620   44050
Boundary for River Rch & Prof#=Chickamauga,1               , 1
Up Type= 0
Dn Type= 1
Dn Known WS=669.4863
Boundary for River Rch & Prof#=Chickamauga,1               , 2
Up Type= 0
Dn Type= 1
Dn Known WS=673.0731
Boundary for River Rch & Prof#=Chickamauga,1               , 3
Up Type= 0
Dn Type= 1
Dn Known WS=674.627
Boundary for River Rch & Prof#=Chickamauga,1               , 4
Up Type= 0
Dn Type= 1
Dn Known WS=679.1569
DSS Import GetInterval= 0
DSS Import GetPeak= 0
DSS Import FillOption= 0

--- SouthChickamauga.f03 (steady flow) ---

Flow Title=Duplicate Effective
Program Version=5.03
Number of Profiles= 4
Profile Names=10-yr,50-yr,100-yr,500-yr
River Rch & RM=Chickamauga,1               ,82389.53
   18070   25240   28620   36620
River Rch & RM=Chickamauga,1               ,77468.57
   18140   25460   28730   36730
River Rch & RM=Chickamauga,1               ,72338.71
   18200   25680   28840   36840
River Rch & RM=Chickamauga,1               ,70655.09
   18230   25750   28870   36870
River Rch & RM=Chickamauga,1               ,66422.72
   18300   26000   29000   37000
River Rch & RM=Chickamauga,1               ,65236.66
   22400   29500   32600   44000
River Rch & RM=Chickamauga,1               ,64750.50
   22410   29510   32610   44010
River Rch & RM=Chickamauga,1               ,63534.37
   22420   29520   32620   44050
Boundary for River Rch & Prof#=Chickamauga,1               , 1
Up Type= 0
Dn Type= 1
Dn Known WS=669.4863
Boundary for River Rch & Prof#=Chickamauga,1               , 2
Up Type= 0
Dn Type= 1
Dn Known WS=673.0731
Boundary for River Rch & Prof#=Chickamauga,1               , 3
Up Type= 0
Dn Type= 1
Dn Known WS=674.627
Boundary for River Rch & Prof#=Chickamauga,1               , 4
Up Type= 0
Dn Type= 1
Dn Known WS=679.1569
DSS Import GetInterval= 0
DSS Import GetPeak= 0
DSS Import FillOption= 0

--- SouthChickamauga.g12 (geometry) ---

Geom Title=Natural Conditions
Program Version=5.03

River Reach=Chickamauga     ,1
Reach XY= 30
2215558.66030213238678.6785441492215190.40021189239338.640150726
2216330.25029439241888.4001430572215414.87023538242894.980150893
2212886.15022722242396.9503070562212552.95994872243235.180257887
2214955.41971073245413.1696683172213643.71039189245900.680176228
2212963.31017789247861.2198903112208333.76038189245455.260135308
2207022.05992131248348.7202276442204808.99971488249215.009833649
2204307.46003555254535.4798357342205180.76012622258200.540418983
2204858.10001038260203.1699438992206436.35013472 260866.04000923
2204801.98004389261886.6396740672200737.09972222260497.779918984
2200607.32964055261332.5000343172202880.01997705262791.509911567
2201063.27000164265302.6797579822203658.62012589266221.579823062
2204402.16030547267792.8201188892203535.86971521268701.190021306
2199362.25962414269823.5099551382201487.65005839270896.720407143
2202396.01996081273229.0300469852193799.78977796276382.029974565
2190443.36998163275466.6397449822185957.62009488275933.100098148

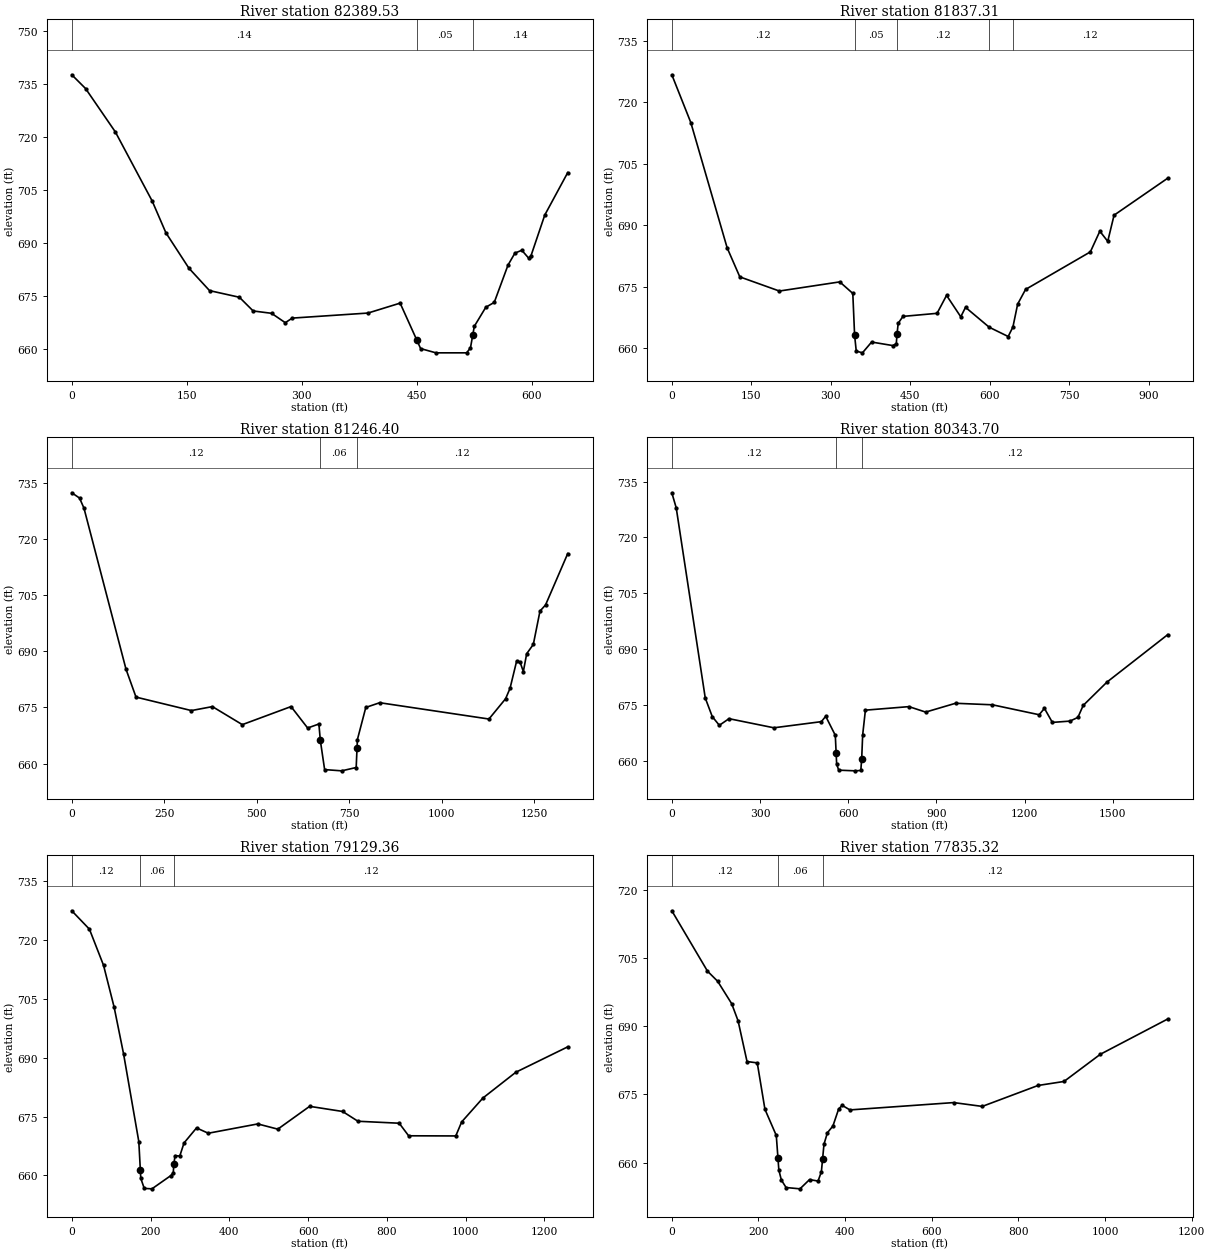
Type RM Length L Ch R = 1 ,82389.53,463.05,552.22,555.99
BEGIN DESCRIPTION:
XS AL
END DESCRIPTION:
XS GIS Cut Line= 2
2215121.67369711242380.8193284572215031.24811384243021.333876625
#Sta/Elev= 30
       0  737.75   17.97  733.86    56.9  721.55  104.82  702.04  122.78  693.02
  152.73  683.02  179.69  676.66  218.62  674.78  236.59   670.9  260.54  670.24
  278.51  667.58   287.5  668.88  386.32  670.31  428.25  673.12     450  662.67
     455  660.25     475  659.05     515  659.05     520  660.45     523  664.11
     525  666.55     540  671.95  551.03  673.33     569   683.9  577.99  687.28
  586.97  688.08  595.96  685.84  598.95  686.53  616.92  698.05  646.87  710.07
#Mann= 3 , 0 , 0
       0     .14       0     450     .05       0     523     .14       0
Bank Sta=450,523
XS Rating Curve= 0 ,0
Exp/Cntr=0.3,0.1

Type RM Length L Ch R = 1 ,81837.31,634.98,590.91,497.1
BEGIN DESCRIPTION:
From HSE Survey 8700
END DESCRIPTION:
XS GIS Cut Line= 4
 2214782.5777598242230.1100229772214639.40391964242508.922238067
2214548.97833636242652.0960782472214428.41089199243089.153064087
#Sta/Elev= 30
       0  726.69   35.82  715.05  104.47   684.5  128.35  677.44  202.98  673.99
     317  676.22   341.6  673.41     345  663.21   348.1  659.36   359.8  658.93
   377.1  661.56   417.2   660.7   423.7  661.16   425.1  663.54   427.3  666.14
   436.3  667.81  500.66  668.56  518.56  672.93   545.4  667.71  554.35  670.02
  599.09  665.17  634.89  662.91  643.83  665.23  652.78  670.81   667.7  674.38
  789.99  683.53  807.89  688.57   822.8   686.1  834.73  692.47  936.15   701.5
#Mann= 5 ,-1 , 0
       0     .12       0     345     .05       0   425.1     .12       0
  599.09     .05       0  643.83     .12       0
Bank Sta=345,425.1
XS Rating Curve= 0 ,0
Exp/Cntr=0.3,0.1

Type RM Length L Ch R = 1 ,81246.40,1050.27,902.71,652.71
BEGIN DESCRIPTION:
From HSE Survey 8600
END DESCRIPTION:
XS GIS Cut Line= 5
2214134.52774635241936.2268773622214036.56669784242569.205960259
2213998.88937142242787.7344531572214021.49576728242900.766432256
2214262.63065602243172.043182075
#Sta/Elev= 30
       0  732.37   20.95  730.96   32.92  728.27  146.66  685.18   173.6  677.75
  323.25  674.15  380.12  675.21  460.93  670.39  592.63  675.22  637.52  669.49
   667.9  670.56   671.8  666.18   683.4  658.37   729.5  658.04   768.7  658.93
     771 664.136     772   666.4   794.7  674.99   832.3  676.25 1127.52  671.89
 1172.51  677.31 1184.51  680.09 1202.51  687.43 1211.51  687.13 1220.51  684.59
 1229.51  689.34  1247.5  691.84  1265.5  700.75  1280.5  702.38 1340.49  716.12
#Mann= 3 , 0 , 0
       0     .12       0   671.8     .06       0     771     .12       0
Bank Sta=671.8,771
XS Rating Curve= 0 ,0
Exp/Cntr=0.3,0.1

Type RM Length L Ch R = 1 ,80343.70,1352.55,1214.33,333.47
BEGIN DESCRIPTION:
From HSE Survey 8500
END DESCRIPTION:
XS GIS Cut Line= 5
2212936.38876802241928.6914120762213200.13005257242335.606536821
2213109.70446929242516.4577033522213320.69749694242915.837362811
2213652.25796893243352.894348621
#Sta/Elev= 30
       0  731.98   14.97  727.92  113.74  676.82  137.69   671.8  161.64  669.48
  194.56  671.26  347.22  668.81   508.7  670.46  523.57   671.9   556.2  666.79
     559 662.067   560.8  659.03   567.8  657.42   623.8  657.24     643  657.34
     646 660.523   649.3  666.91   658.6  673.55  806.76   674.5   863.6  673.03
   965.3   675.4 1090.94  674.99 1249.72  672.32 1267.71  674.03 1294.69  670.26
 1354.64  670.61 1381.62  671.61 1399.61  674.82 1480.55   681.1  1687.4  693.86
#Mann= 3 , 0 , 0
       0     .12       0     559     .06       0     646     .12       0
Bank Sta=559,646
XS Rating Curve= 0 ,0
Exp/Cntr=0.3,0.1

Type RM Length L Ch R = 1 ,79129.36,1351.78,1294.05,556.44
BEGIN DESCRIPTION:
From HSE Survey 8400
END DESCRIPTION:
XS GIS Cut Line= 4
2212326.01608093243232.326904252  2212521.938178243254.933300063
2212665.11201817243285.0751611592213576.90331617243367.965279177
#Sta/Elev= 30
       0   727.4   44.82  722.71   80.68   713.5  107.58  702.83  131.48  690.96
   170.2  668.61     174 661.496   175.2  659.25     184   656.7   203.5  656.59
   251.7  659.98   257.7  660.73     259 662.805   262.2  665.03   274.2  664.95
     285  668.28  316.66   672.1  346.53  670.75  472.19  673.12  523.05  671.79
  603.84   677.6  687.61  676.29  726.51   673.8  831.23   673.3  855.17   670.1
  974.85  670.06  989.81  673.63 1043.66  679.71 1127.44  686.29 1259.08  692.75
#Mann= 3 , 0 , 0
       0     .12       0     174     .06       0     259     .12       0
Bank Sta=174,259
XS Rating Curve= 0 ,0
Exp/Cntr=0.3,0.1

Type RM Length L Ch R = 1 ,77835.32,443.94,366.75,209.74
BEGIN DESCRIPTION:
From HSE Survey 8300
END DESCRIPTION:
XS GIS Cut Line= 4
2213083.09485751244435.8819982862213184.82363871 244346.86931476
2213324.70071286244219.7083382612213566.30656813243435.548983335
#Sta/Elev= 30
       0  715.33   82.28  702.07  105.79  699.84  138.13  694.92   152.9  691.16
  173.57  682.21   197.2  681.91  214.92  671.71   241.1  665.97     245 660.953
     247  658.38   252.8  656.18   263.7  654.53   295.8  654.24   317.8  656.27
   337.5  655.95   345.2     658     348 660.823   351.2  664.05   359.1  666.56
   371.8  668.04   384.9  671.74  393.09  672.59  411.06  671.58  650.63  673.19
  716.51  672.35  845.28  676.95  905.17  677.83  989.02   683.8 1144.74  691.56
#Mann= 3 , 0 , 0
       0     .12       0     245     .06       0     348     .12       0
Bank Sta=245,348
XS Rating Curve= 0 ,0
Exp/Cntr=0.3,0.1

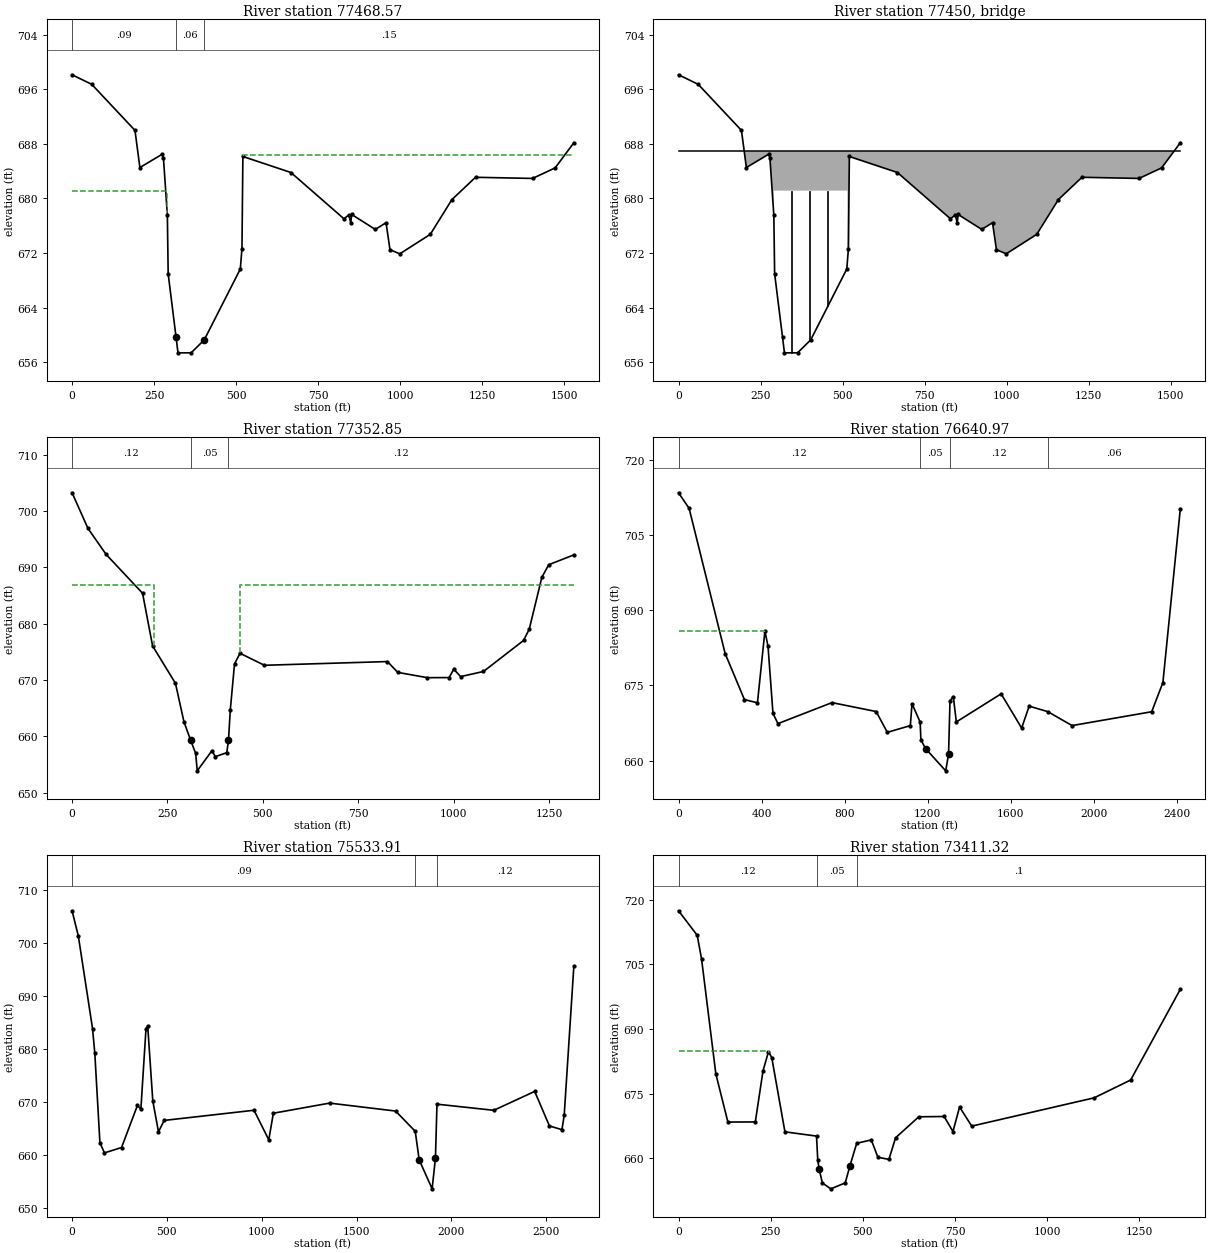
Type RM Length L Ch R = 1 ,77468.57,66.99,115.72,364.34
BEGIN DESCRIPTION:
XS AK
END DESCRIPTION:
XS GIS Cut Line= 4
2213337.41681047244728.3522441832213557.82916975 244626.62346299
2213617.17095876 243914.521994742214062.23437642243554.232561365
#Sta/Elev= 30
       0  698.15   59.94  696.75  191.81  689.99  206.79  684.54  275.64  686.52
  278.63  685.92  290.59  677.52     293  668.95     317  659.67     323  657.35
     363  657.35     403  659.25     513  669.65     518  672.65  520.81  686.16
  667.31  683.81  828.76  677.03  843.71  677.56  849.69  676.45  852.68  677.65
  924.43  675.46  957.32  676.44  969.31  672.48  999.29  671.88 1092.23  674.74
 1158.19  679.84 1230.14  683.11 1404.03  682.94 1472.98  684.49 1529.95  688.18
#Mann= 3 , 0 , 0
       0     .09       0     317     .06       0     403     .15       0
#XS Ineff= 2 , 0
       0     290  681.15  520.82       0  686.39
Permanent Ineff=
       F       F
Bank Sta=317,403
XS Rating Curve= 0 ,0
Exp/Cntr=0.5,0.3

Type RM Length L Ch R = 3 ,77450   ,,,
BEGIN DESCRIPTION:
Louisville and Nashville Railroad
END DESCRIPTION:
Bridge Culvert--1,0,-1,-1, 0
Deck Dist Width WeirC Skew NumUp NumDn MinLoCord MaxHiCord MaxSubmerge Is_Ogee
2,15,2.6,0, 6, 6, , , 0.98, 0, 0,0,,
       0     290     290     515     515 1529.95
  686.95  686.95  686.95  686.95  686.95  686.95
     600     600  681.15  681.15     600     600
       0     215     215     440     440 1314.93
  686.95  686.95  686.95  686.95  686.95  686.95
     600     600  681.15  681.15     600     600
Pier Skew, UpSta & Num, DnSta & Num=  ,345, 2 ,270, 2 , 0 , 0 , 0 ,,
       2       2
     600  681.15
       2       2
     600  681.15
Pier Skew, UpSta & Num, DnSta & Num=  ,400, 2 ,325, 2 , 0 , 0 , 0 ,,
       2       2
     600  681.15
       2       2
     600  681.15
Pier Skew, UpSta & Num, DnSta & Num=  ,455, 2 ,380, 2 , 0 , 0 , 0 ,,
       2       2
     600  681.15
       2       2
     600  681.15
BR Coef=-1 , 0 , 0 ,, 0 ,,,0.8,-1,,0,
WSPro=,,,, 1 ,,,, 0 ,,,, 0 ,,,,-1 ,-1 ,-1 , 0 , 0 , 0 , 0 , 0
BC Design=,, 0 ,, 0 ,,,,,,
BC Use User HTab Curves=0
BC User HTab FreeFlow(D)= 0

Type RM Length L Ch R = 1 ,77352.85,574.6,711.87,825.09
BEGIN DESCRIPTION:
From HSE Survey 8200
END DESCRIPTION:
XS GIS Cut Line= 5
2213430.66819321244787.6940332062213591.73876342244664.771755949
2213723.13843912244465.5528927892213943.55079834 244075.59256494
2214291.12413403243829.748010412
#Sta/Elev= 30
       0  703.23   41.72   696.9   89.39  692.28  184.74   685.4     211  676.06
     271  669.41   293.1  662.61   310.4  659.38   323.9  656.98     328  653.89
   366.3  657.45   375.5  656.42   405.4  657.11   409.9  659.32   414.6  664.67
   425.7  672.86   440.1  674.75  503.98  672.62   826.5  673.28  853.37  671.36
  931.18  670.42  988.14  670.44 1000.14  671.94 1018.13  670.61 1078.09  671.52
 1183.02  677.02 1198.01  679.02 1230.99  688.21 1248.98  690.46 1314.93  692.21
#Mann= 3 , 0 , 0
       0     .12       0   310.4     .05       0   409.9     .12       0
#XS Ineff= 2 , 0
       0     215  686.95     440       0  686.95
Permanent Ineff=
       F       F
Bank Sta=310.4,409.9
XS Rating Curve= 0 ,0
Exp/Cntr=0.5,0.3

Type RM Length L Ch R = 1 ,76640.97,552.6,1107.06,1525.31
XS GIS Cut Line= 4
2213133.95924814 245330.247532832214210.58884896245033.538587734
 2214320.7950286244834.3197245752215172.77357097244181.560045332
#Sta/Elev= 30
       0  713.42    50.9  710.32  224.55  681.35  317.37  672.17  380.24  671.52
  416.17  685.84  431.14  682.79  455.09   669.4  479.04  667.37  739.52  671.56
   952.1  669.78 1005.99  665.63 1116.77  666.97    1125  671.33  1164.1  667.67
  1167.7  664.14  1190.5  662.38  1287.3  657.95    1301 661.245    1308  671.94
  1323.9  672.77 1338.44   667.7  1554.3  673.31 1653.23  666.48 1689.21  670.86
 1779.15  669.76 1896.08  666.98 2279.83  669.74 2333.79  675.57 2417.74  710.24
#Mann= 4 ,-1 , 0
       0     .12       0  1164.1     .05       0    1308     .12       0
 1779.15     .06       0
#XS Ineff= 2 , 0
          418.57  685.78
Permanent Ineff=
       F       F
Bank Sta=1190.5,1301
XS Rating Curve= 0 ,0
Exp/Cntr=0.3,0.1

Type RM Length L Ch R = 1 ,75533.91,977.11,2122.59,1797.84
BEGIN DESCRIPTION:
From HSE Survey 8000
END DESCRIPTION:
XS GIS Cut Line= 4
2213104.28835364245614.2403803172214876.06462584 245635.43387638
2215058.32869211245669.3434701112215698.37227371245923.665423065
#Sta/Elev= 30
       0  706.06   32.98   701.3  107.93  683.82  119.93  679.15  146.91  662.25
  170.89  660.34  260.84  661.35  344.79  669.31  362.78   668.6  389.76  683.75
  398.75  684.34  425.74  670.14  455.72  664.32   485.7  666.47  959.41  668.39
 1037.36   662.8 1061.35  667.83 1358.17  669.74 1705.95  668.24  1809.6  664.42
  1830.4  659.02  1898.7  653.55  1916.2  659.41  1924.2  669.54 2223.81  668.38
  2439.4  671.95 2517.26  665.43 2583.13  664.72 2595.11  667.45 2646.02  695.64
#Mann= 3 ,-1 , 0
       0     .09       0  1809.6     .05       0  1924.2     .12       0
#XS Ineff= 2 , 0
          397.96  684.24
Permanent Ineff=
       F       F
Bank Sta=1830.4,1916.2
XS Rating Curve= 0 ,0
Exp/Cntr=0.3,0.1

Type RM Length L Ch R = 1 ,73411.32,704.9,1072.61,1460.58
BEGIN DESCRIPTION:
From HSE Survey 7900
END DESCRIPTION:
XS GIS Cut Line= 4
2213125.48184969 246483.173719572213434.90689243246525.560711712
2213629.88705637246538.2768093792214469.14950113 246690.86998114
#Sta/Elev= 30
       0  717.42   50.57  711.75   62.46  706.24  101.13  679.62  133.85  668.44
  208.21  668.47  229.03  680.28   243.9  684.76  252.83  683.38  288.52  666.17
   374.2  665.19   377.5  659.69     381 657.673     390  654.31     413  652.96
   452.1  654.34     465 658.362   483.1  663.51  522.67  664.31  540.63  660.27
  570.56  659.79  588.52  664.79  651.37  669.66  720.21  669.73  744.16  666.25
  762.12  671.93  795.04   667.5 1127.27  674.06 1226.04  678.19 1360.73  699.22
#Mann= 3 ,-1 , 0
       0     .12       0   374.2     .05       0   483.1      .1       0
#XS Ineff= 2 , 0
          245.34  684.83
Permanent Ineff=
       F       F
Bank Sta=381,465
XS Rating Curve= 0 ,0
Exp/Cntr=0.3,0.1

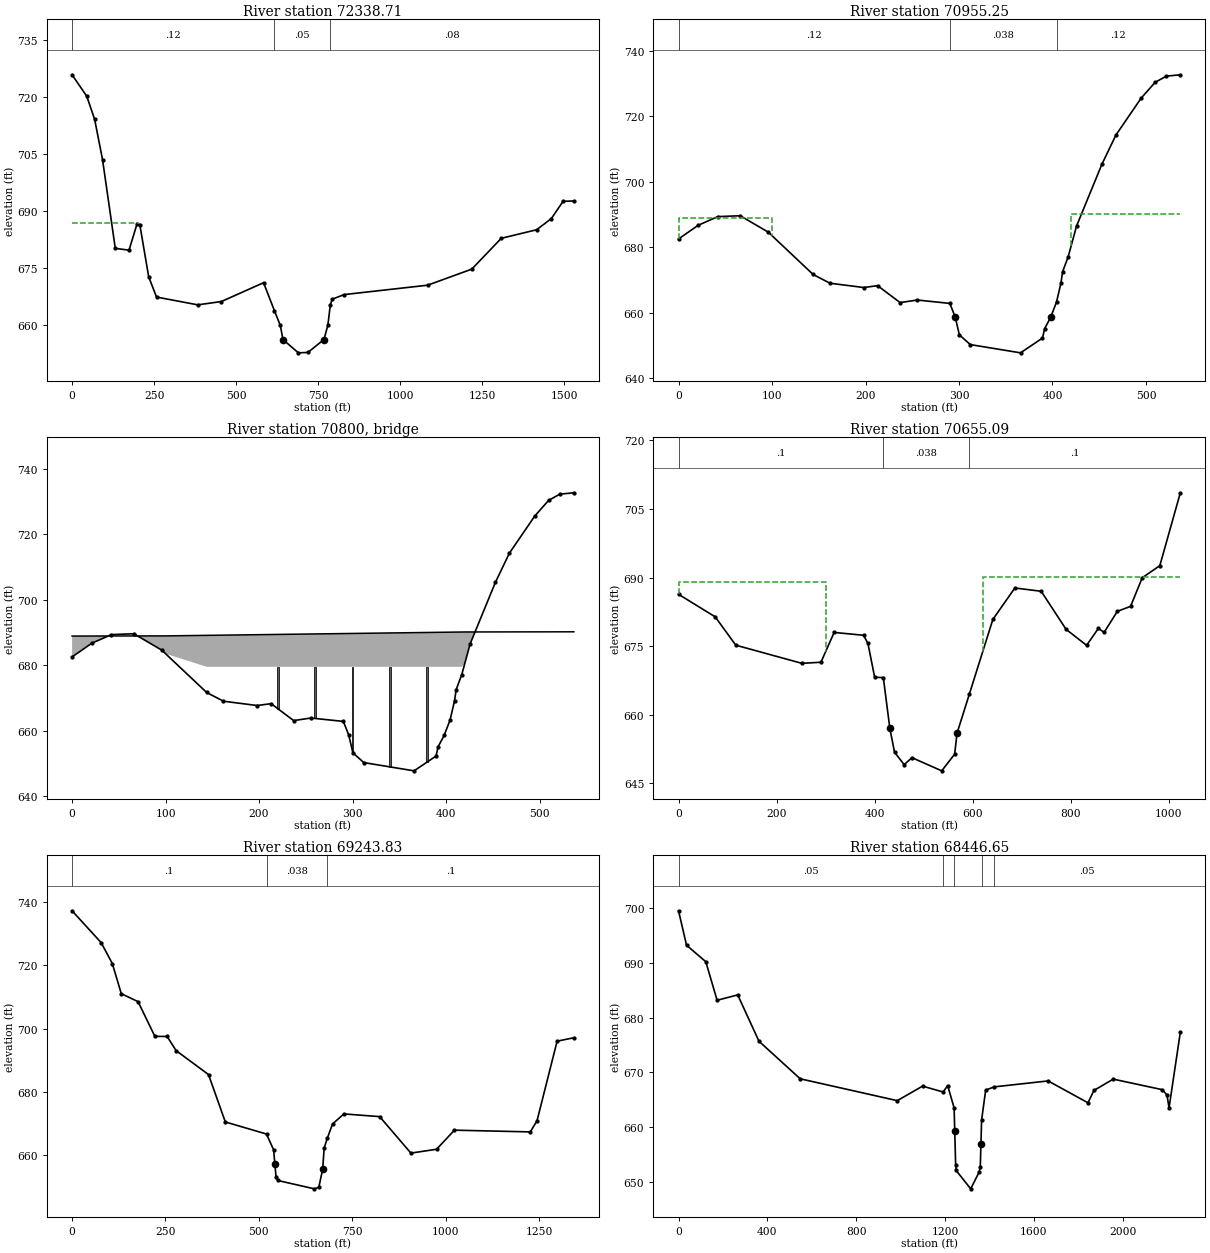
Type RM Length L Ch R = 1 ,72338.71,833.68,1383.45,1435.12
BEGIN DESCRIPTION:
XS AJ
END DESCRIPTION:
XS GIS Cut Line= 3
2212964.41127948 246843.463152932213528.15827519 248178.65340592
2213523.91957602248259.188691035
#Sta/Elev= 30
       0  725.83   44.92  720.17   68.87  714.08   92.83  703.53  131.76  680.15
  173.68  679.67  197.64  686.47  206.62  686.36  233.57  672.68  257.52  667.33
  383.29  665.28  455.16  666.15  583.92  671.11  616.86  663.76     635  659.85
     643  656.15     690  652.65     719  652.75     768  656.15     780  659.95
  787.54  665.36  793.53  666.78  829.47  667.98    1084  670.45 1218.75  674.68
 1308.58  682.79 1416.39  685.04 1461.27  687.98 1497.12  692.53 1529.97  692.62
#Mann= 3 ,-1 , 0
       0     .12       0  616.86     .05       0  787.54     .08       0
#XS Ineff= 2 , 0
          201.17  686.72
Permanent Ineff=
       F       F
Bank Sta=643,768
XS Rating Curve= 0 ,0
Exp/Cntr=0.3,0.1

Type RM Length L Ch R = 1 ,70955.25,275.83,300.16,327.8
XS GIS Cut Line= 4
 2212515.1091626247343.6296603832212345.56119394247500.461531371
2212209.92281908247631.8612070682212125.14883472247712.396492168
#Sta/Elev= 30
       0  682.51      21  686.69   41.99  689.34   65.99  689.61   95.98  684.59
  143.98  671.64  161.97  668.97  197.97  667.66  212.96  668.22     237  663.05
   255.4  663.83   290.2   662.8     296 658.572   300.4  653.17   312.1   650.2
   365.8  647.68   389.3  652.19   391.6  655.07     398 658.528   404.3   663.2
   409.1  669.11  410.82  672.48  416.81   677.1   425.8  686.51  452.79  705.31
  467.78  714.25  494.76  725.55  509.75   730.4  521.75   732.3  536.74  732.72
#Mann= 3 ,-1 , 0
       0     .12       0   290.2    .038       0   404.3     .12       0
#XS Ineff= 2 , 0
       0     100  688.95     420       0  690.15
Permanent Ineff=
       F       F
Bank Sta=296,398
XS Rating Curve= 0 ,0
Exp/Cntr=0.5,0.3

Type RM Length L Ch R = 3 ,70800   ,,,
BEGIN DESCRIPTION:
Louisville and Nashville Railroad
END DESCRIPTION:
Bridge Culvert--1,0,-1,-1, 0
Deck Dist Width WeirC Skew NumUp NumDn MinLoCord MaxHiCord MaxSubmerge Is_Ogee
150,18,2.6,0, 6, 6, , , 0.98, 0, 0,0,,
       0     100     100     420     420  536.74
   688.9  688.95  688.95  690.15  690.15   690.2
     600     600   679.5   679.5     600     600
       0     300     300     620     620 1023.46
  688.75  688.95  688.95  690.15  690.15  690.55
     600     600   679.5   679.5     600     600
Pier Skew, UpSta & Num, DnSta & Num=  ,220, 2 ,420, 2 , 0 , 0 , 0 ,,
       2       2
     600   679.5
       2       2
     600   679.5
Pier Skew, UpSta & Num, DnSta & Num=  ,260, 2 ,460, 2 , 0 , 0 , 0 ,,
       2       2
     600   679.5
       2       2
     600   679.5
Pier Skew, UpSta & Num, DnSta & Num=  ,300, 2 ,500, 2 , 0 , 0 , 0 ,,
       2       2
     600   679.5
       2       2
     600   679.5
Pier Skew, UpSta & Num, DnSta & Num=  ,340, 2 ,540, 2 , 0 , 0 , 0 ,,
       2       2
     600   679.5
       2       2
     600   679.5
Pier Skew, UpSta & Num, DnSta & Num=  ,380, 2 ,580, 2 , 0 , 0 , 0 ,,
       2       2
     600   679.5
       2       2
     600   679.5
BR Coef=-1 , 0 , 0 ,, 0 ,,,0.8,0,1.2,1,
WSPro=,,,, 1 ,,,, 0 ,,,, 0 ,,,,-1 ,-1 ,-1 , 0 , 0 , 0 , 0 , 0
BC Design=,, 0 ,, 0 ,,,,,,
BC Use User HTab Curves=0
BC User HTab FreeFlow(D)= 0

Type RM Length L Ch R = 1 ,70655.09,1477.28,1411.26,1326.67
BEGIN DESCRIPTION:
XS AI
From HSE Survey 7700
END DESCRIPTION:
XS GIS Cut Line= 4
2212489.67696731247080.8303090182212154.81972924 247267.33307451
2211997.98785825247436.8810431362211599.55013198247530.132425904
#Sta/Elev= 30
       0  686.35   74.86  681.41  116.78  675.22  251.54  671.25  290.46  671.49
  317.41  678.01   377.3  677.39  386.29  675.62     400  668.21   417.7  668.13
     431 657.031   440.5  651.83   460.2  649.09   476.1  650.62   536.8  647.74
   563.2  651.39     568 655.957     593  664.47  641.13  680.86  685.94  687.73
   739.7  687.01  790.48  678.68   832.3  675.19  856.19  678.87  868.14  678.04
  895.02  682.63   921.9   683.7   945.8  689.97  981.64  692.61 1023.46  708.55
#Mann= 3 ,-1 , 0
       0      .1       0   417.7    .038       0     593      .1       0
#XS Ineff= 2 , 0
       0     300  688.95     620       0  690.15
Permanent Ineff=
       F       F
Bank Sta=431,568
XS Rating Curve= 0 ,0
Exp/Cntr=0.5,0.3

Type RM Length L Ch R = 1 ,69243.83,792.28,797.18,852.81
BEGIN DESCRIPTION:
From HSE Survey 7600
END DESCRIPTION:
XS GIS Cut Line= 4
2211207.94142106246352.9514603322210853.77455327246684.511932313
2210725.67164364 246872.898564162210567.42687286247483.271251231
#Sta/Elev= 30
       0   737.3   77.86  727.21  107.81  720.57  131.77  711.03  176.69  708.51
  221.61  697.52  254.55  697.47  278.51     693  365.36   685.4  410.28  670.39
   520.6  666.56   539.6  661.56     543 657.078   546.2  652.86   550.6  651.85
   648.9   649.2   660.6  649.67     671 655.457     675  662.15   683.4  665.23
   697.4  669.76   727.9  672.94  823.53  672.08  907.21  660.52  975.94  661.74
 1023.75  667.79 1226.96  667.24  1244.9  670.78 1298.69  695.99 1343.51  697.07
#Mann= 3 ,-1 , 0
       0      .1       0   520.6    .038       0   683.4      .1       0
Bank Sta=543,671
XS Rating Curve= 0 ,0
Exp/Cntr=0.3,0.1

Type RM Length L Ch R = 1 ,68446.65,1284.67,1259.06,1027.68
BEGIN DESCRIPTION:
From HSE Survey 7500
END DESCRIPTION:
XS GIS Cut Line= 4
2211034.62571979245365.8055095822210220.79547037246232.384015962
2210070.08616489246390.6287866832209595.35185272247098.962522328
#Sta/Elev= 30
       0   699.5   35.93  693.22  122.77  690.21  173.68  683.17  266.51  684.15
  362.33  675.69  547.99  668.84  985.19  664.85 1098.98   667.5 1191.81  666.43
  1212.2   667.6  1241.2  663.53    1244  659.33  1248.1  653.18  1250.2  652.12
    1316  648.76    1354  651.83  1359.1  652.77    1362 656.973    1365  661.32
  1383.4  666.79 1422.31  667.37 1664.65  668.45 1844.17  664.46  1871.1  666.72
 1957.86  668.78 2179.27  666.85 2200.21  665.86 2209.19  663.52 2260.05  677.35
#Mann= 5 ,-1 , 0
       0     .05       0 1191.81     .12       0  1241.2    .038       0
    1365     .12       0 1422.31     .05       0
Bank Sta=1244,1362
XS Rating Curve= 0 ,0
Exp/Cntr=0.3,0.1

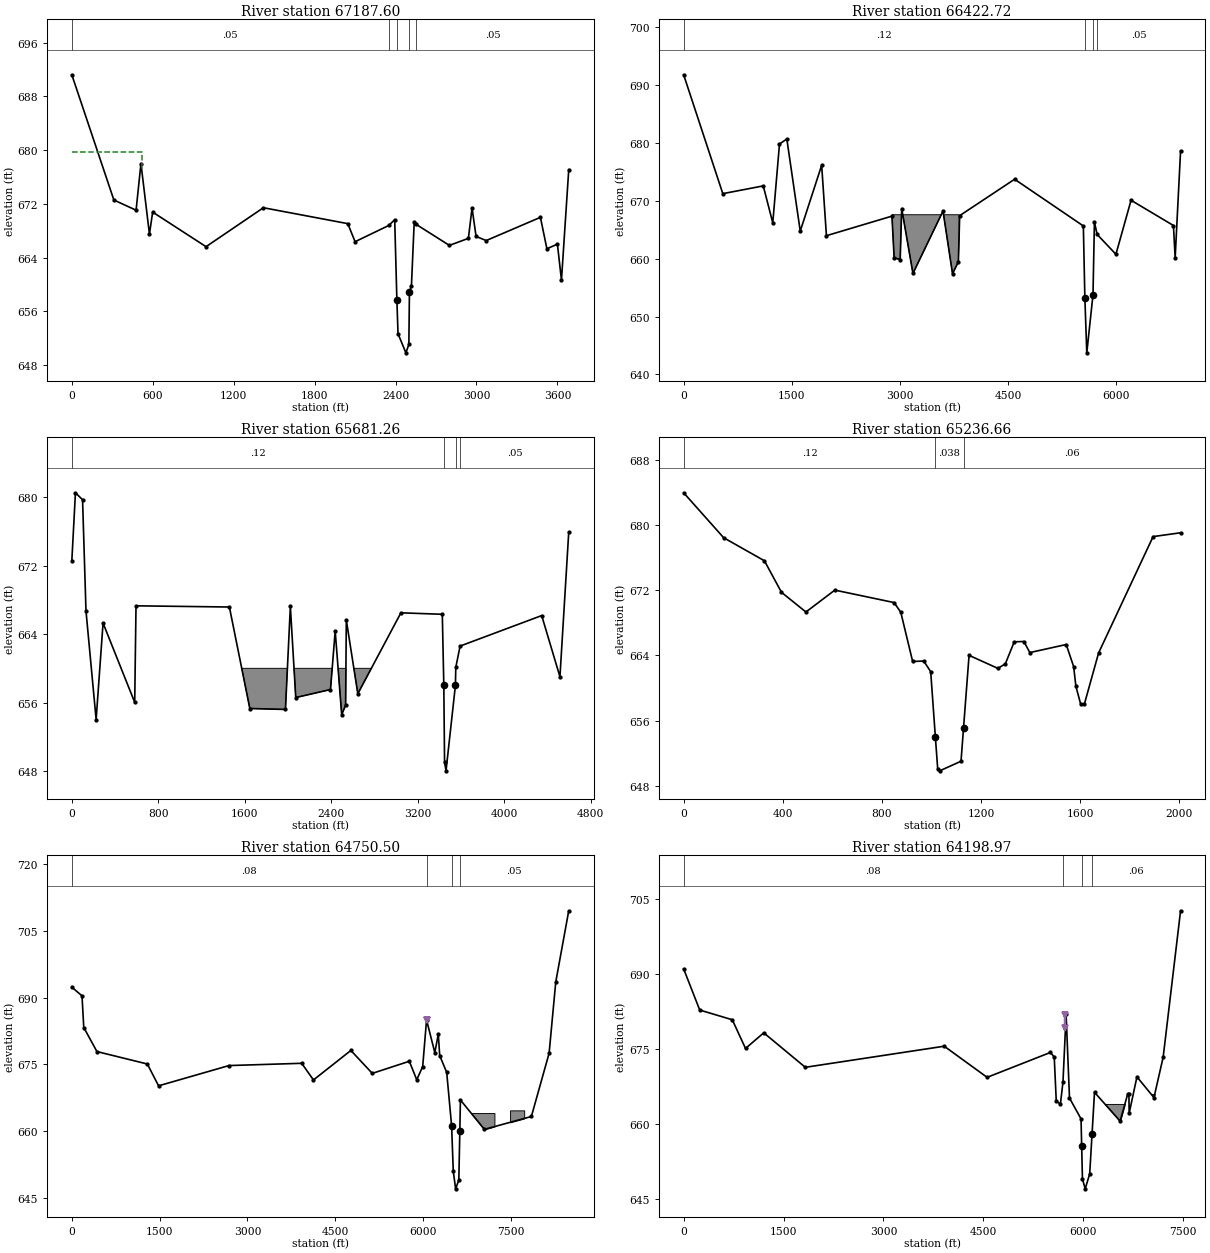
Type RM Length L Ch R = 1 ,67187.60,1141.18,764.88,504.07
BEGIN DESCRIPTION:
From HSE Survey 7400
END DESCRIPTION:
XS GIS Cut Line= 5
2211087.37397669244348.517697766 2209866.6286025244770.503753066
2209150.75940165245531.5857456032209060.33381833 245735.04330796
2208864.41172126246842.756703034
#Sta/Elev= 30
       0  691.22  311.67  672.57  476.49  671.05  512.45     678  575.39   667.5
  599.36  670.77  994.94  665.62 1420.37  671.42 2046.09  669.05 2099.98  666.36
    2350  668.78  2393.7  669.64    2410 657.618  2418.3  652.66  2476.7  649.81
  2498.7  651.06    2503 658.864  2517.9  659.83 2538.37  669.27 2553.22  668.94
 2799.13  665.81 2940.12  666.86 2967.12  671.37 2997.12  667.15 3072.11  666.53
 3474.08  669.99 3522.08  665.31 3600.07     666 3630.07  660.63 3684.06  677.09
#Mann= 5 ,-1 , 0
       0     .05       0    2350     .12       0    2410    .038       0
    2503     .12       0 2553.22     .05       0
#XS Ineff= 2 , 0
          517.83  679.79
Permanent Ineff=
       F       F
Bank Sta=2410,2503
XS Rating Curve= 0 ,0
Exp/Cntr=0.3,0.1

Type RM Length L Ch R = 1 ,66422.72,600.54,741.47,320.15
BEGIN DESCRIPTION:
From HSE Survey 7300
END DESCRIPTION:
XS GIS Cut Line= 4
2204859.31192881241091.9407891042208355.76781535245321.848628834
2208375.86238943245522.7943694592208466.28797269246718.421526045
#Sta/Elev= 30
       0  691.76   542.8  671.23 1103.58  672.57 1235.53  666.19  1328.5   679.8
 1430.46  680.67 1616.39  664.76 1913.28  676.13 1979.26  663.97 2887.89  667.35
 2917.88  660.16 3001.85  659.84 3022.84  668.66 3178.77  657.45  3595.6  668.23
 3727.55   657.4 3808.52  659.45 3826.51  667.43 4588.24  673.72  5541.1  665.65
    5562  653.29  5588.7  643.74 5674.78 653.768  5694.6  666.35 5731.85  664.19
 5992.64  660.76 6202.47  670.09 6789.99  665.73 6813.97  660.17 6888.91  678.61
#Mann= 4 ,-1 , 0
       0     .12       0    5562    .038       0 5674.78     .12       0
 5731.85     .05       0
#XS Ineff= 2 , 0
         1428.67  680.65
Permanent Ineff=
       F       F
#Block Obstruct= 1 ,-1
  2889.7 3819.02  667.59
Bank Sta=5562,5674.78
XS Rating Curve= 0 ,0
Exp/Cntr=0.3,0.1

Type RM Length L Ch R = 1 ,65681.26,988.49,444.59,268.93
BEGIN DESCRIPTION:
Channel Surveyed 2017.  Overbanks from LiDAR.
END DESCRIPTION:
XS GIS Cut Line= 3
2204851.12036556243919.1549398152208115.16895555246078.658494815
2208430.47180264 246685.43812114
#Sta/Elev= 30
       0  672.56   33.38  680.53   99.37  679.72  130.98  666.72  224.86  654.01
  288.95  665.29  581.86  656.02  593.84  667.31 1457.77  667.17 1646.92   655.3
 1976.57  655.19  2021.9  667.25 2071.78  656.58  2393.2  657.52 2436.77  664.36
 2496.74  654.59 2533.19  655.67 2539.64  665.64 2646.12  657.03 3044.76  666.49
 3427.76  666.32 3441.68  658.01 3448.63  649.01  3462.1  648.01 3549.08  658.01
 3552.59  660.11 3592.23   662.6 4347.29  666.17 4516.15  659.01 4597.56  675.93
#Mann= 4 ,-1 , 0
       0     .12       0 3441.68    .038       0 3552.59     .12       0
 3592.23     .05       0
#Block Obstruct= 1 ,-1
    1500    3000     660
Bank Sta=3441.68,3549.08
XS Rating Curve= 0 ,0
Exp/Cntr=0.3,0.1

Type RM Length L Ch R = 1 ,65236.66,494.09,486.16,508.59
BEGIN DESCRIPTION:
XS AH - Surveyed Section 2017
END DESCRIPTION:
XS GIS Cut Line= 4
2206587.44529802245884.4967025222207481.65384372246226.104461551
2207672.55229728246276.3408967262208406.00425053246708.374239028
#Sta/Elev= 30
       0  683.97  161.53  678.45  326.06  675.62  394.86  671.75  493.58  669.33
  610.24  672.02  849.55  670.49  876.47   669.3  924.34  663.26   969.2  663.31
  997.18  662.01 1016.02  654.01 1025.66  650.01 1033.58  649.83 1119.63  651.01
 1129.66  655.05 1152.09  664.01 1268.54  662.41 1298.51  662.97 1334.48  665.67
 1373.44  665.71 1397.42  664.35 1544.29  665.34 1574.26  662.63 1583.25  660.23
  1602.7  658.01 1617.43  658.01 1675.06  664.31 1894.97  678.59 2005.88  679.06
#Mann= 3 , 0 , 0
       0     .12       0 1016.02    .038       0 1129.66     .06       0
Bank Sta=1016.02,1129.66
XS Rating Curve= 0 ,0
Exp/Cntr=0.5,0.3

Type RM Length L Ch R = 1 ,64750.50,614.08,551.53,766.27
BEGIN DESCRIPTION:
XS AG - Channel Surveyed 2017.  Overbanks from Effective FIS Model.
END DESCRIPTION:
XS GIS Cut Line= 5
2201001.15370916245794.0711192492207119.95151061246607.901368707
2207692.64687136246788.7525352542208606.94999112 247964.28511779
2208506.47712083248165.230858415
#Sta/Elev= 30
       0  692.39  173.96  690.44  203.96  683.31  428.91   677.9 1289.73   675.1
 1481.69  670.19 2684.42  674.75 3926.12  675.26 4127.07  671.51 4765.97  678.15
 5131.91  672.99 5764.81  675.72 5890.79  671.55 5992.77  674.53 6058.76  685.02
 6199.63  677.67 6259.39   681.8 6283.29  676.99  6402.8  673.226486.633   661.2
6514.983  651.016555.093  647.016609.843  649.016626.983  660.016637.133  667.01
 7045.98  660.39 7849.06  663.29 8151.71  677.51 8265.57  693.57 8487.21  709.58
#Mann= 4 ,-1 , 0
       0     .08       0 6058.76     .05       06486.633    .038       0
6626.983     .05       0
Levee=-1,6058.63,685.07,0,,,Levee 1,
#Block Obstruct= 2 ,-1
 6807.82 7218.24  664.06 7485.34 7726.38  664.67
Bank Sta=6486.633,6626.983
XS Rating Curve= 0 ,0
Exp/Cntr=0.5,0.3

Type RM Length L Ch R = 1 ,64198.97,566.91,664.6,545.68
BEGIN DESCRIPTION:
Channel Surveyed 2017.  Overbanks from LiDAR.
END DESCRIPTION:
XS GIS Cut Line= 4
2201415.13609581246601.2365178912207083.13985163 247209.12998715
 2207707.9699668247330.7199670672208302.98321247248285.264317811
#Sta/Elev= 30
       0  691.02  241.34  682.79  730.41  680.84  928.92   675.1 1202.81  678.23
 1826.75  671.33 3912.86  675.55 4556.87  669.32 5506.81   674.3 5564.84  673.39
 5594.83  664.68 5656.94   663.9 5696.06  668.41  5743.2  681.93 5793.95  665.17
5967.389  661.015976.749  655.525988.379  649.016029.769  647.016097.349  650.01
6132.689  658.01 6169.46  666.33 6553.89  660.55 6667.45  665.96 6686.17   665.9
 6689.76  662.13  6806.7  669.42 7062.15  665.27 7200.52  673.35 7461.87  702.65
#Mann= 4 ,-1 , 0
       0     .08       0 5696.06     .05       05976.749    .037       0
6132.689     .06       0
Levee=-1,5733.62,681.88,0,,,,
#Block Obstruct= 2 ,-1
    6314    6645     664    6850    7100     666
Bank Sta=5976.749,6132.689
XS Rating Curve= 0 ,0
Exp/Cntr=0.3,0.1

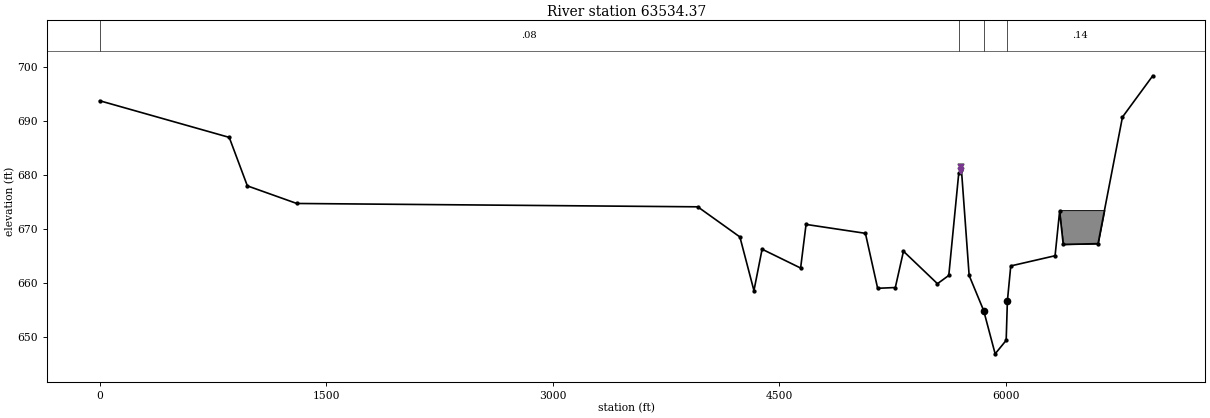
Type RM Length L Ch R = 1 ,63534.37,0,0,0
BEGIN DESCRIPTION:
XS AF
END DESCRIPTION:
XS GIS Cut Line= 3
2201392.99790338247049.9819980412207029.52592735247783.433951259
2208144.77478772248426.460321188
#Sta/Elev= 30
       0  693.83  857.86  687.04  977.84  678.06 1304.79   674.8 3959.35  674.18
 4238.31   668.6 4331.29  658.66 4385.28  666.33 4640.24  662.84 4676.24  670.92
 5069.17  669.27 5150.16  659.09 5267.14  659.23 5321.13  665.95  5546.1  659.94
 5621.08  661.47 5687.07  680.41 5705.03  680.99 5755.92  661.46    5852 654.963
    5928  646.95    6001  649.45    6009 656.723 6031.34  663.23 6324.71  665.12
 6354.65  673.32  6378.6  667.22 6609.11  667.36 6770.77   690.8 6971.34  698.45
#Mann= 4 ,-1 , 0
       0     .08       0 5687.07     .05       0    5852    .036       0
    6009     .14       0
Levee=-1,5700.33,681.54,0,,,Levee 1,
#Block Obstruct= 1 ,-1
    6357 6685.34  673.57
Bank Sta=5852,6009
XS Rating Curve= 0 ,0
Exp/Cntr=0.3,0.1
LCMann Table=0

Chan Stop Cuts=-1
Use User Specified Reach Order=0
Composite Channel Slope=5

--- SouthChickamauga.g06 (geometry) ---

Geom Title=Duplicate Effective
Program Version=5.03

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
River Reach=Chickamauga     ,1
Reach XY= 30
2215670.30850992238059.0897393822215190.40226133239338.644889474
2216375.84668541 241783.185610192215414.86511083242894.978161797
2212830.03510918242439.0379986762212602.06502758243561.352246359
2214962.43217973245504.3587876562213643.71293873245900.676006377
2212963.30992609247861.2187077852208333.76365437245455.257539332
2207022.05887742248348.7239591032204808.99547029249215.010269031
2204307.46129087254535.4812494222205180.76206483258200.538714498
2204858.09671861260203.1682001952206436.35112946260866.035052732
2204801.98100623261886.6395717112200737.09909043260497.775690228
2200607.33150554261332.4969119432202880.01785707262791.505433917
2201063.27166867265302.6835630982203658.62336642266221.578353375
2204402.15655549267792.8183001432203535.87024558268701.191394344
2199362.26413704269823.5056420272201487.64674355270896.718641371
2202396.01983778273229.0279373082193799.79414696276382.029526874
2190443.37310001275466.6419686232185957.62334135275933.103827804