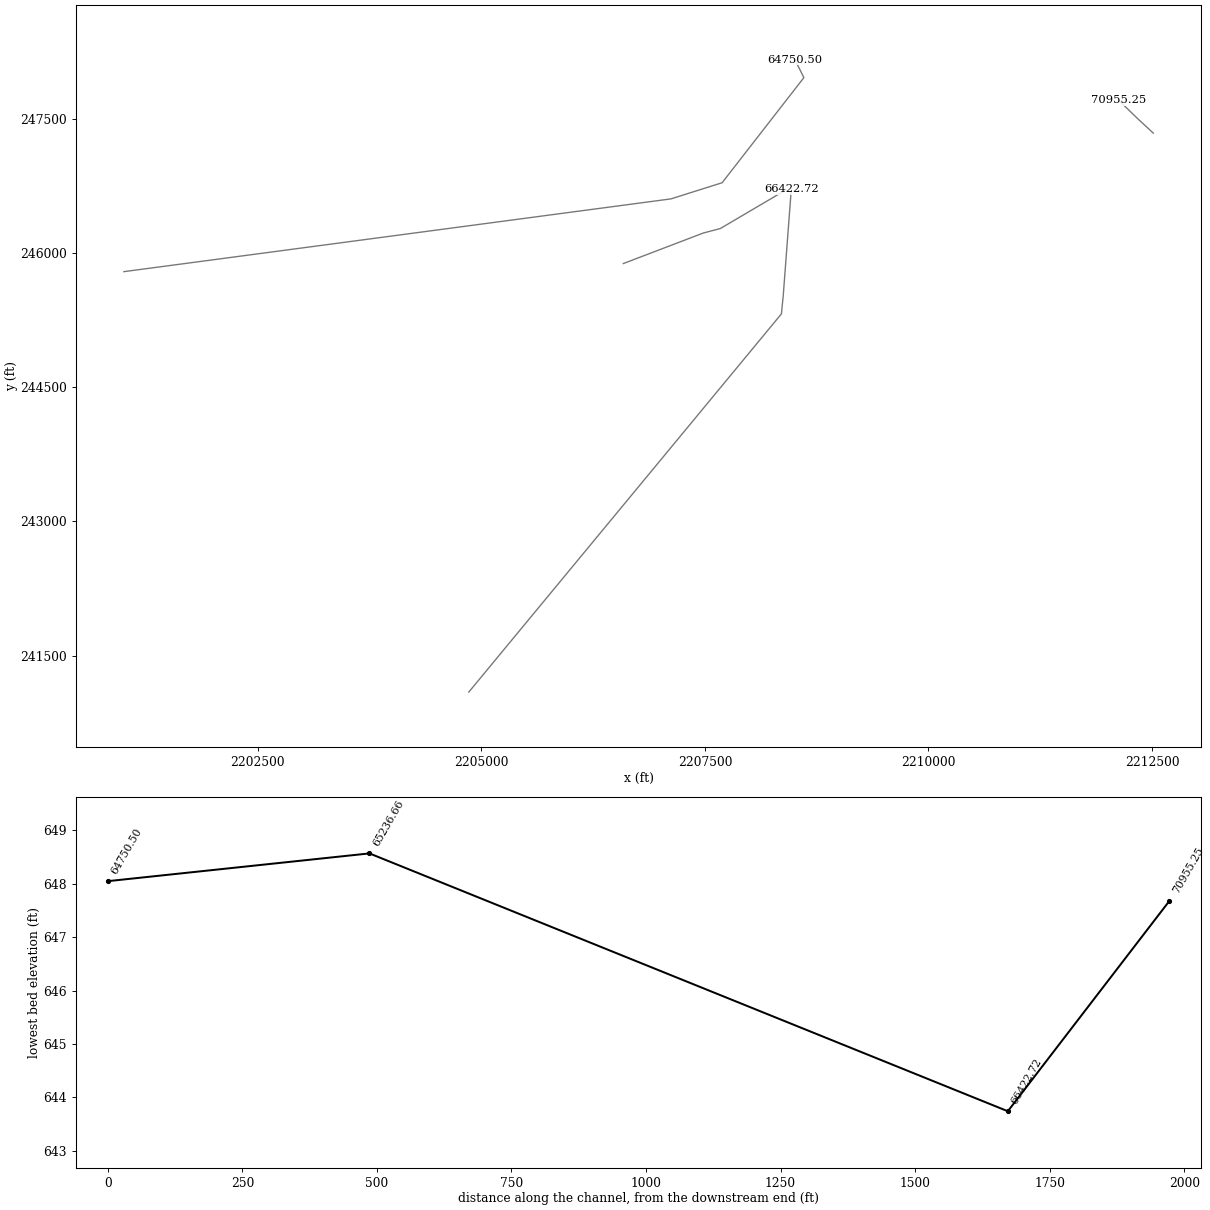
HEC-RAS study SouthChickamauga.prj: South Chickamauga

--- SouthChickamauga.g06 (geometry) --- (continued)

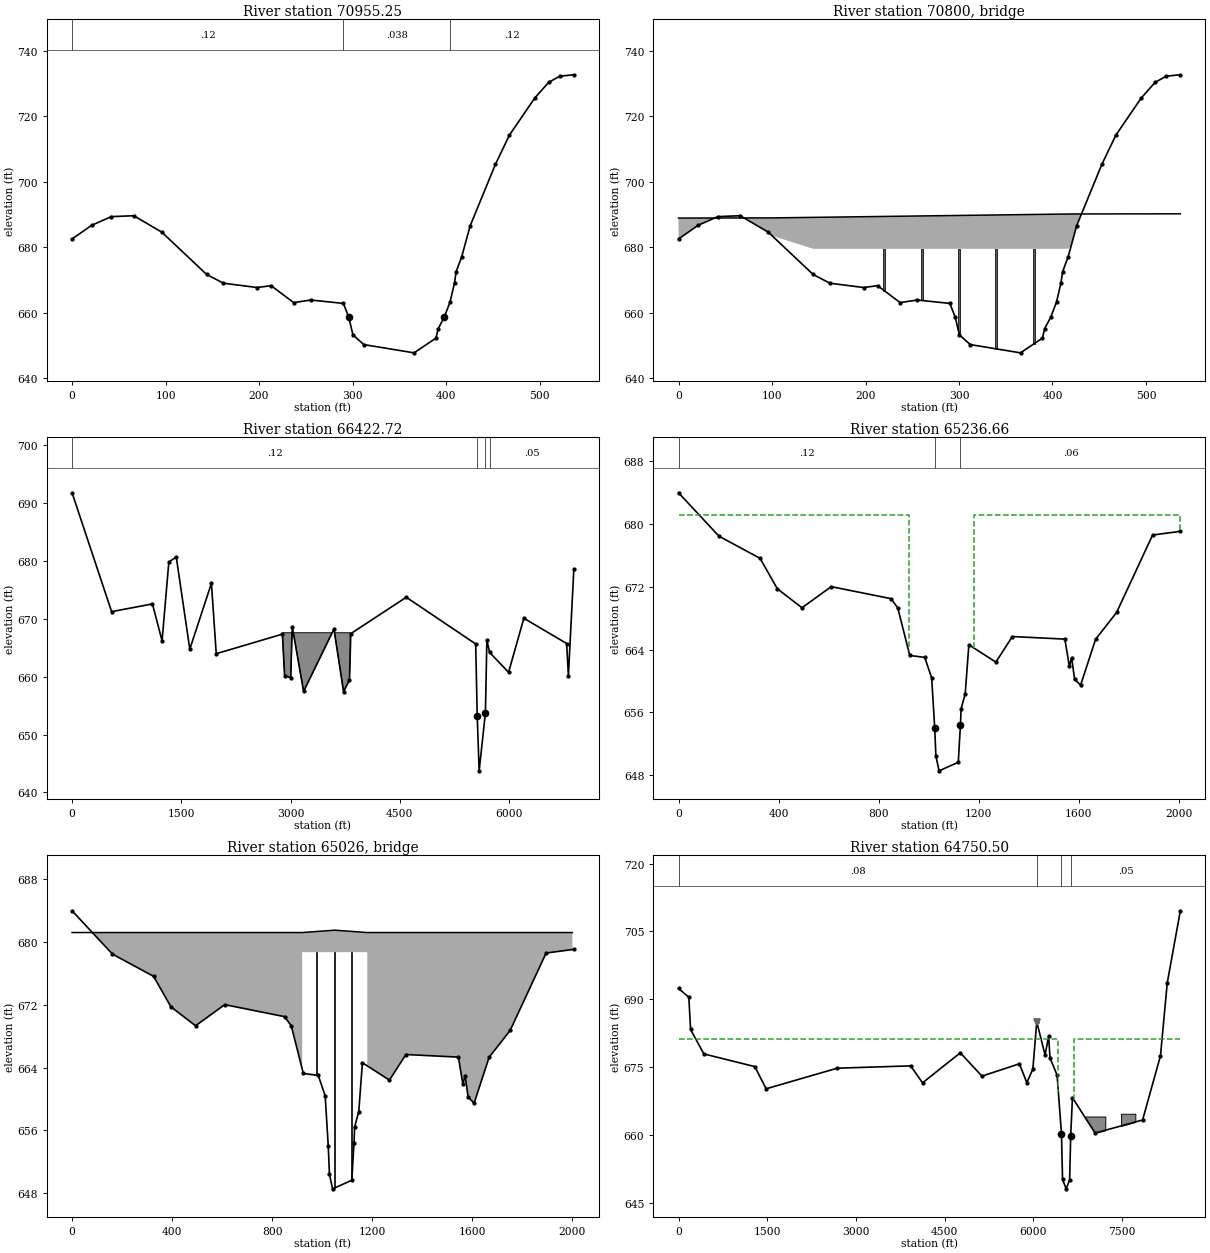
Type RM Length L Ch R = 1 ,70955.25,275.83,300.16,327.8
XS GIS Cut Line= 4
 2212515.1091626247343.6296603832212345.56119394247500.461531371
2212209.92281908247631.8612070682212125.14883472247712.396492168
#Sta/Elev= 30
       0  682.51      21  686.69   41.99  689.34   65.99  689.61   95.98  684.59
  143.98  671.64  161.97  668.97  197.97  667.66  212.96  668.22     237  663.05
   255.4  663.83   290.2   662.8     296 658.572   300.4  653.17   312.1   650.2
   365.8  647.68   389.3  652.19   391.6  655.07     398 658.528   404.3   663.2
   409.1  669.11  410.82  672.48  416.81   677.1   425.8  686.51  452.79  705.31
  467.78  714.25  494.76  725.55  509.75   730.4  521.75   732.3  536.74  732.72
#Mann= 3 ,-1 , 0
       0     .12       0   290.2    .038       0   404.3     .12       0
Bank Sta=296,398
XS Rating Curve= 0 ,0
Exp/Cntr=0.5,0.3

Type RM Length L Ch R = 3 ,70800   ,,,
BEGIN DESCRIPTION:
Louisville and Nashville Railroad
END DESCRIPTION:
Bridge Culvert--1,0,-1,-1, 0
Deck Dist Width WeirC Skew NumUp NumDn MinLoCord MaxHiCord MaxSubmerge Is_Ogee
150,18,2.6,0, 6, 6, , , 0.98, 0, 0,0,,
       0     100     100     420     420  536.74
   688.9  688.95  688.95  690.15  690.15   690.2
     600     600   679.5   679.5     600     600
       0     300     300     620     620 1023.46
  688.75  688.95  688.95  690.15  690.15  690.55
     600     600   679.5   679.5     600     600
Pier Skew, UpSta & Num, DnSta & Num=  ,220, 2 ,420, 2 , 0 , 0 , 0 ,,
       2       2
     600   679.5
       2       2
     600   679.5
Pier Skew, UpSta & Num, DnSta & Num=  ,260, 2 ,460, 2 , 0 , 0 , 0 ,,
       2       2
     600   679.5
       2       2
     600   679.5
Pier Skew, UpSta & Num, DnSta & Num=  ,300, 2 ,500, 2 , 0 , 0 , 0 ,,
       2       2
     600   679.5
       2       2
     600   679.5
Pier Skew, UpSta & Num, DnSta & Num=  ,340, 2 ,540, 2 , 0 , 0 , 0 ,,
       2       2
     600   679.5
       2       2
     600   679.5
Pier Skew, UpSta & Num, DnSta & Num=  ,380, 2 ,580, 2 , 0 , 0 , 0 ,,
       2       2
     600   679.5
       2       2
     600   679.5
BR Coef=-1 , 1 , 0 ,, 0 ,,,0.8,-1,1.2,0,
WSPro=,,,, 1 ,,,, 0 ,,,, 0 ,,,,-1 ,-1 ,-1 , 0 , 0 , 0 , 0 , 0
BC Design=,, 0 ,, 0 ,,,,,,
BC Use User HTab Curves=0
BC User HTab FreeFlow(D)= 0

Type RM Length L Ch R = 1 ,66422.72,1589.03,1186.06,589.08
BEGIN DESCRIPTION:
From HSE Survey 7300
END DESCRIPTION:
XS GIS Cut Line= 4
2204859.31192881241091.9407891042208355.76781535245321.848628834
2208375.86238943245522.7943694592208466.28797269246718.421526045
#Sta/Elev= 30
       0  691.76   542.8  671.23 1103.58  672.57 1235.53  666.19  1328.5   679.8
 1430.46  680.67 1616.39  664.76 1913.28  676.13 1979.26  663.97 2887.89  667.35
 2917.88  660.16 3001.85  659.84 3022.84  668.66 3178.77  657.45  3595.6  668.23
 3727.55   657.4 3808.52  659.45 3826.51  667.43 4588.24  673.72  5541.1  665.65
    5562  653.29  5588.7  643.74 5674.78 653.768  5694.6  666.35 5731.85  664.19
 5992.64  660.76 6202.47  670.09 6789.99  665.73 6813.97  660.17 6888.91  678.61
#Mann= 4 ,-1 , 0
       0     .12       0    5562    .038       0 5674.78     .12       0
 5731.85     .05       0
#XS Ineff= 2 , 0
         1428.67  680.65
Permanent Ineff=
       F       F
#Block Obstruct= 1 ,-1
  2889.7 3819.02  667.59
Bank Sta=5562,5674.78
XS Rating Curve= 0 ,0
Exp/Cntr=0.3,0.1

Type RM Length L Ch R = 1 ,65236.66,494.09,486.16,508.59
BEGIN DESCRIPTION:
XS AH
From HSE Survey 7200
END DESCRIPTION:
XS GIS Cut Line= 4
2206587.44529802245884.4967025222207481.65384372246226.104461551
2207672.55229728246276.3408967262208406.00425053246708.374239028
#Sta/Elev= 30
       0  683.97  161.53  678.45  326.06  675.62  394.86  671.75  493.58  669.33
  610.24  672.02  849.55  670.49  876.47   669.3  924.34  663.26  984.16  663.01
  1011.9   660.4    1024 654.051  1028.8  650.44  1041.5  648.57  1118.2  649.66
    1127 654.433  1129.6  656.48    1146  658.39 1160.63  664.62 1268.54  662.41
 1334.48  665.67 1544.29  665.34 1562.27  661.88 1571.27  662.96 1583.25  660.23
 1607.23  659.48 1667.18  665.32  1751.1  668.73 1894.97  678.59 2005.88  679.06
#Mann= 3 , 0 , 0
       0     .12       0    1024    .038       0    1127     .06       0
#XS Ineff= 2 , 0
       0     920   681.2    1180       0   681.2
Permanent Ineff=
       F       F
Bank Sta=1024,1127
XS Rating Curve= 0 ,0
Exp/Cntr=0.5,0.3

Type RM Length L Ch R = 3 ,65026   ,,,
BEGIN DESCRIPTION:
Interstate 75
END DESCRIPTION:
Bridge Culvert--1,0,-1,-1, 0
Deck Dist Width WeirC Skew NumUp NumDn MinLoCord MaxHiCord MaxSubmerge Is_Ogee
150,135,2.6,0, 7, 7, , , 0.98, 0, 0,0,,
       0     920     920    1050    1180    1180 1999.88
   681.2   681.2   681.2   681.5   681.2   681.2   681.2
     600     600   678.7   678.7   678.7     600     600
       0    6426    6426    6556    6686    6686 8487.21
   681.2   681.2   681.2   681.5   681.2   681.2   681.2
     600     600   678.7   678.7   678.7     600     600
Pier Skew, UpSta & Num, DnSta & Num=  ,977, 2 ,6483, 2 , 0 , 0 , 0 ,,
       5       5
     600   678.7
       5       5
     600   678.7
Pier Skew, UpSta & Num, DnSta & Num=  ,1050, 2 ,6556, 2 , 0 , 0 , 0 ,,
       5       5
     600   678.7
       5       5
     600   678.7
Pier Skew, UpSta & Num, DnSta & Num=  ,1117, 2 ,6623, 2 , 0 , 0 , 0 ,,
       5       5
     600   678.7
       5       5
     600   678.7
BR Coef=-1 , 1 , 0 ,, 0 ,,,0.8,-1,1.2,0,
WSPro=,,,, 1 ,,,, 0 ,,,, 0 ,,,,-1 ,-1 ,-1 , 0 , 0 , 0 , 0 , 0
BC Design=,, 0 ,, 0 ,,,,,,
BC Use User HTab Curves=0
BC User HTab FreeFlow(D)= 0

Type RM Length L Ch R = 1 ,64750.50,1180.99,1216.13,1311.95
BEGIN DESCRIPTION:
XS AG
END DESCRIPTION:
XS GIS Cut Line= 5
2201001.15370916245794.0711192492207119.95151061246607.901368707
2207692.64687136246788.7525352542208606.94999112 247964.28511779
2208506.47712083248165.230858415
#Sta/Elev= 30
       0  692.39  173.96  690.44  203.96  683.31  428.91   677.9 1289.73   675.1
 1481.69  670.19 2684.42  674.75 3926.12  675.26 4127.07  671.51 4765.97  678.15
 5131.91  672.99 5764.81  675.72 5890.79  671.55 5992.77  674.53 6058.76  685.02
 6199.63  677.67 6259.39   681.8 6283.29  676.99  6402.8  673.22    6477 660.275
    6495  650.15    6556  648.05    6615  650.05    6633  659.85 6662.74  668.22
 7045.98  660.39 7849.06  663.29 8151.71  677.51 8265.57  693.57 8487.21  709.58
#Mann= 4 ,-1 , 0
       0     .08       0 6058.76     .05       0    6477    .038       0
    6633     .05       0
Levee=-1,6058.63,685.07,0,,,Levee 1,
#XS Ineff= 2 , 0
       0    6426   681.2    6686       0   681.2
Permanent Ineff=
       F       F
#Block Obstruct= 2 ,-1
 6807.82 7218.24  664.06 7485.34 7726.38  664.67
Bank Sta=6477,6633
XS Rating Curve= 0 ,0
Exp/Cntr=0.5,0.3

--- SouthChickamauga.g09 (geometry) ---

Geom Title=Existing
Program Version=5.03

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
River Reach=Chickamauga     ,1

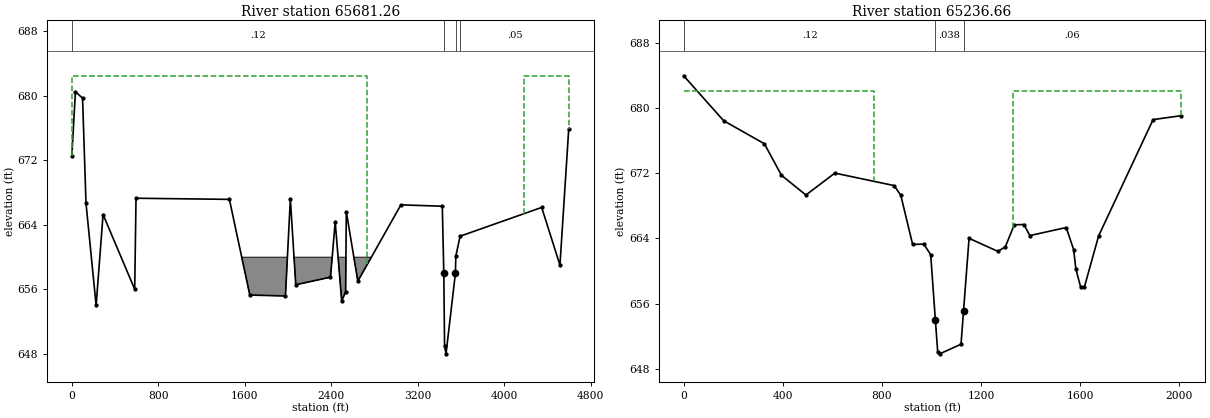
Type RM Length L Ch R = 1 ,65681.26,988.49,444.59,268.93
BEGIN DESCRIPTION:
Channel Surveyed 2017.  Overbanks from LiDAR
END DESCRIPTION:
XS GIS Cut Line= 3
2204851.12036556243919.1549398152208115.16895555246078.658494815
2208430.47180264 246685.43812114
#Sta/Elev= 30
       0  672.56   33.38  680.53   99.37  679.72  130.98  666.72  224.86  654.01
  288.95  665.29  581.86  656.02  593.84  667.31 1457.77  667.17 1646.92   655.3
 1976.57  655.19  2021.9  667.25 2071.78  656.58  2393.2  657.52 2436.77  664.36
 2496.74  654.59 2533.19  655.67 2539.64  665.64 2646.12  657.03 3044.76  666.49
 3427.76  666.32 3441.68  658.01 3448.63  649.01  3462.1  648.01 3549.08  658.01
 3552.59  660.11 3592.23   662.6 4347.29  666.17 4516.15  659.01 4597.56  675.93
#Mann= 4 ,-1 , 0
       0     .12       0 3441.68    .038       0 3552.59     .12       0
 3592.23     .05       0
#XS Ineff= 2 , 0
       0 2735.63   682.5 4184.25       0   682.5
Permanent Ineff=
       F       F
#Block Obstruct= 1 ,-1
    1500    3000     660
Bank Sta=3441.68,3549.08
XS Rating Curve= 0 ,0
Exp/Cntr=0.3,0.1

Type RM Length L Ch R = 1 ,65236.66,494.09,486.16,508.59
BEGIN DESCRIPTION:
XS AH - - Surveyed Section 2017
END DESCRIPTION:
XS GIS Cut Line= 4
2206587.44529802245884.4967025222207481.65384372246226.104461551
2207672.55229728246276.3408967262208406.00425053246708.374239028
#Sta/Elev= 30
       0  683.97  161.53  678.45  326.06  675.62  394.86  671.75  493.58  669.33
  610.24  672.02  849.55  670.49  876.47   669.3  924.34  663.26   969.2  663.31
  997.18  662.01 1016.02  654.01 1025.66  650.01 1033.58  649.83 1119.63  651.01
 1129.66  655.05 1152.09  664.01 1268.54  662.41 1298.51  662.97 1334.48  665.67
 1373.44  665.71 1397.42  664.35 1544.29  665.34 1574.26  662.63 1583.25  660.23
  1602.7  658.01 1617.43  658.01 1675.06  664.31 1894.97  678.59 2005.88  679.06
#Mann= 3 , 0 , 0
       0     .12       0 1016.02    .038       0 1129.66     .06       0
#XS Ineff= 2 , 0
       0  769.75   682.1 1329.19       0   682.1
Permanent Ineff=
       F       F
Bank Sta=1016.02,1129.66
XS Rating Curve= 0 ,0
Exp/Cntr=0.5,0.3