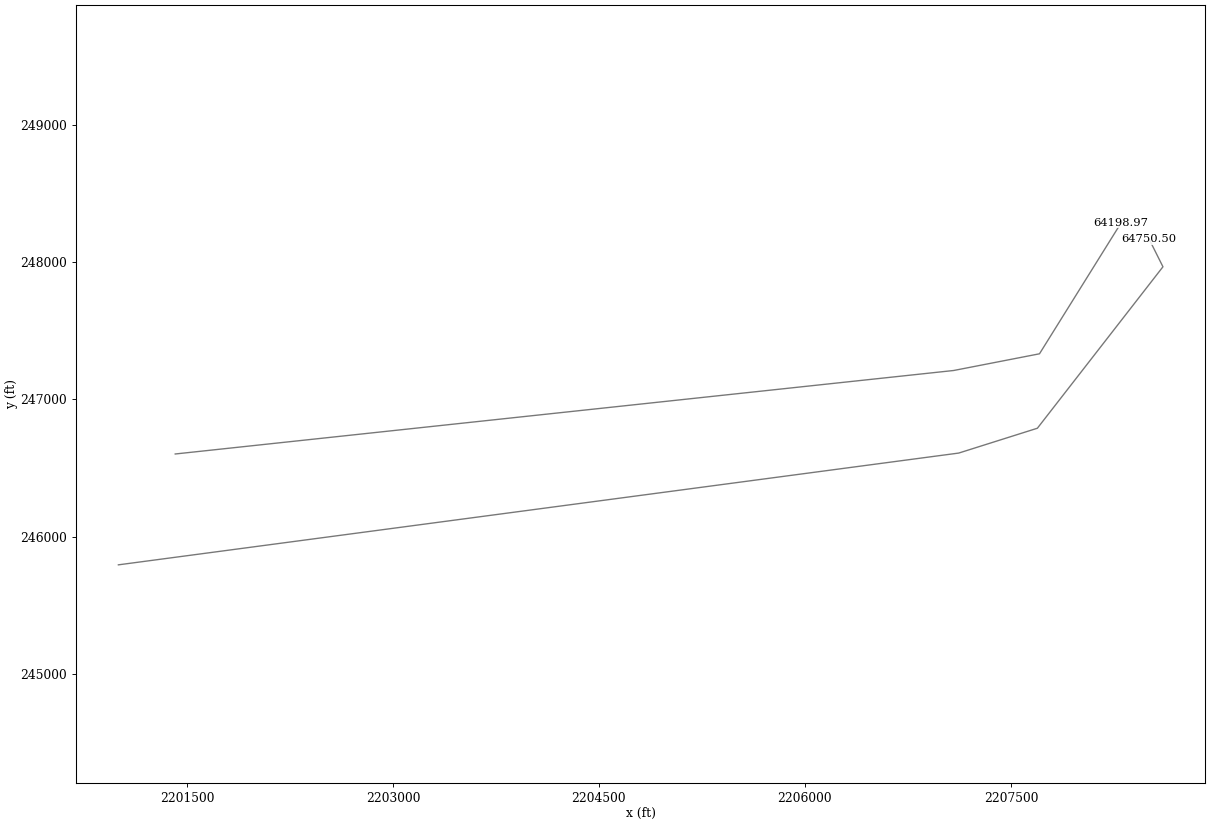
HEC-RAS study SouthChickamauga.prj: South Chickamauga

--- SouthChickamauga.g09 (geometry) --- (continued)

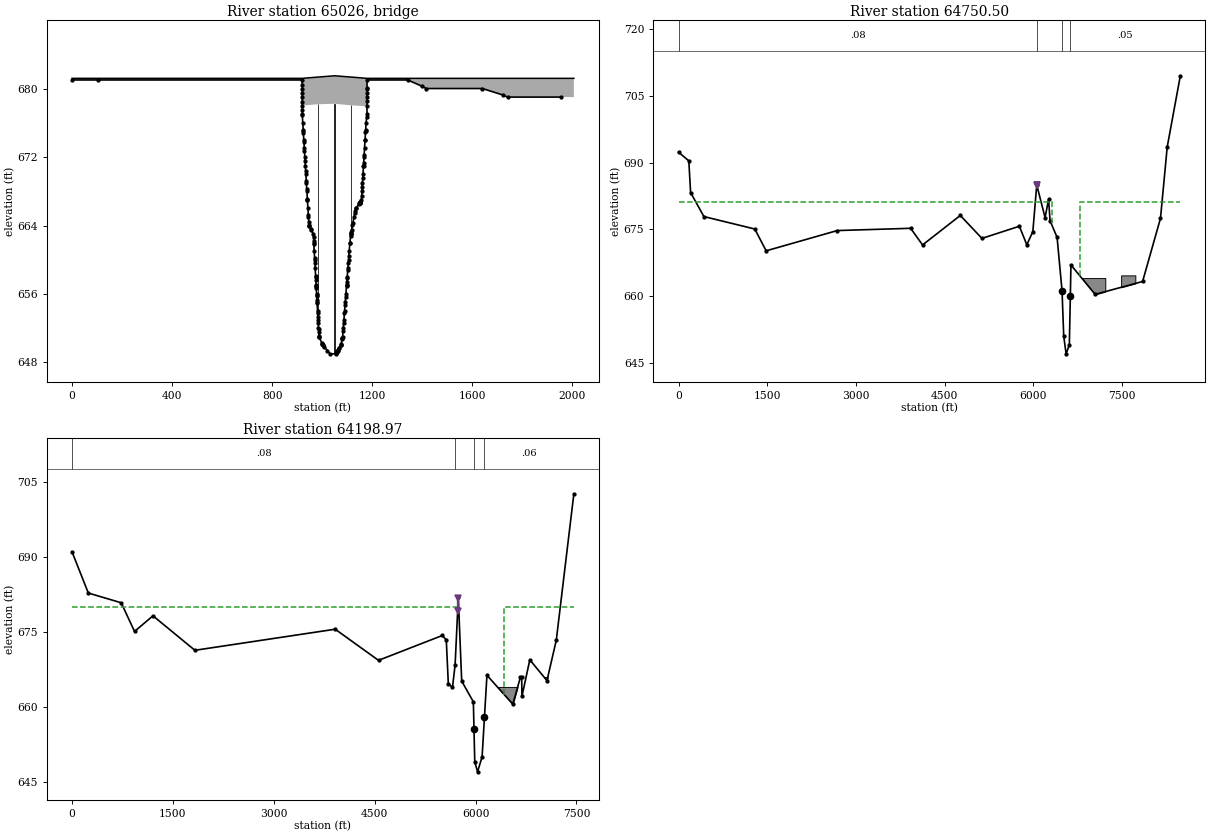
Type RM Length L Ch R = 3 ,65026   ,,,
BEGIN DESCRIPTION:
Existing Interstate 75 Bridge
END DESCRIPTION:
Bridge Culvert--1,0,-1,-1, 0
Deck Dist Width WeirC Skew NumUp NumDn MinLoCord MaxHiCord MaxSubmerge Is_Ogee
150.25,130,2.6,0, 10, 9, , , 0.98, 0, 0,0,,
       0     920     920  983.37 1049.27 1115.48 1178.94 1178.94 1999.88    2006
   681.2   681.2   681.2  681.35   681.5  681.35   681.2   681.2   681.2   681.2
     600     600  678.03  678.17  678.23  678.05  677.93     600     600     600
       0    6426    6426 6489.37 6555.27 6621.48 6684.94 6684.94 8487.21
   681.2   681.2   681.2  681.35   681.5  681.35   681.2   681.2   681.2
     600     600  678.03  678.17  678.23  678.05  677.93     600     600
Pier Skew, UpSta & Num, DnSta & Num=  ,983.37, 2 ,6489.37, 2 , 0 , 0 , 0 ,,
       3       3
     600   678.7
       3       3
     600   678.7
Pier Skew, UpSta & Num, DnSta & Num=  ,1049.27, 2 ,6555.27, 2 , 0 , 0 , 0 ,,
       3       3
     600   678.7
       3       3
     600   678.7
Pier Skew, UpSta & Num, DnSta & Num=  ,1115.48, 2 ,6621.48, 2 , 0 , 0 , 0 ,,
       3       3
     600   678.7
       3       3
     600   678.7
BR Coef=-1 , 1 , 1 ,0.9, 0 ,,,0.8,0,1.2,0,
WSPro=,,,, 1 ,,,, 0 ,,,, 0 ,,,,-1 ,-1 ,-1 , 0 , 0 , 0 , 0 , 0
BR U #Sta/Elev= 182
       0  681.01  102.61  681.01     920  681.01  920.03  680.46  920.05  680.01
  920.08   679.5   920.1  679.01  920.13  678.48  920.15  678.01  920.18  677.48
   920.2  677.01  920.39  676.92  922.31  676.01   924.1  675.15  924.37  675.01
  924.72  674.84  926.43  674.01  926.92  673.77  928.48  673.01  929.16  672.68
  930.54  672.01  931.44  671.57  932.59  671.01   933.8  670.43  934.65  670.01
  936.28  669.22  936.71  669.01  938.24  668.27  938.76  668.01  940.58  667.13
  940.82  667.01  940.95  666.95  942.86  666.01  944.42  665.25  944.91  665.01
  946.13  664.42  946.96  664.01  948.43  663.93   949.1  663.89  954.27   663.6
   956.1   663.5  964.81  663.01  965.35  662.62   965.9  662.23   966.2  662.01
  966.42   661.9  968.08  661.01   969.7  660.15  969.96  660.01   970.6  659.67
  971.84  659.01  973.57   658.1  973.72  658.01  974.37  657.67  975.61  657.01
  975.74  656.94  975.86  656.88   976.3  656.65  977.49  656.01  977.71   655.9
  978.04  655.73  978.81  655.32   979.4  655.01  979.58  654.92   981.3  654.01
  981.67  653.82  982.64  653.31  983.21  653.01  983.94  652.63  985.12  652.01
  985.31  651.91  985.86  651.62  986.77  651.15  987.03  651.01  988.06  650.94
  997.84  650.31 1000.26  650.16 1001.05  650.11 1002.75  650.01 1002.85  650.01
 1007.83  649.84 1020.89   649.4 1031.17  649.01 1054.43  649.01 1055.59  649.08
 1055.97   649.1 1056.78  649.14 1056.92  649.15 1058.36  649.22 1059.82   649.3
  1060.3  649.32 1061.77   649.4 1062.66  649.45 1067.96  649.72 1068.19  649.74
 1074.29  650.01 1074.38  650.01    1076  650.21 1079.64  650.75 1080.35  650.84
 1080.59  650.88 1081.48  651.01 1083.25  651.68 1084.13  652.01 1085.74  652.62
 1086.78  653.01 1088.73  653.75 1089.43  654.01 1091.27  654.71 1092.08  655.01
  1093.8  655.66 1094.73  656.01 1097.15  656.93 1097.38  657.01 1097.58  657.09
  1098.5  657.44 1099.79  657.92 1100.02  658.01    1102  658.76 1102.67  659.01
 1104.19  659.59 1105.32  660.01 1106.33   660.4 1107.96  661.01 1110.53  661.98
 1110.61  662.01 1113.34  662.77 1114.06  662.97 1114.23  663.01  1114.8   663.1
 1115.32  663.19 1117.15  663.47 1120.64  664.01 1122.67  664.33 1127.08  665.01
 1129.74  665.43 1131.76  665.74 1133.54  666.01 1134.92  666.01 1147.36  666.53
 1148.57   666.6 1149.35  666.62 1149.93  666.65 1150.67  666.69 1151.16  666.71
 1152.27  666.77 1152.55  666.78 1156.86  667.01 1157.69  667.41 1158.93  668.01
 1159.88  668.48 1160.99  669.01 1162.15  669.57 1163.06  670.01 1164.98  670.95
 1165.12  671.01 1165.63  671.26 1167.17  672.01  1167.6  672.22 1169.22  673.01
 1171.23  673.99 1171.27  674.01 1173.04  674.88 1173.32  675.01 1173.61  675.16
 1175.37  676.01 1177.67  676.64 1179.01  677.01 1179.07  678.01 1179.11  678.58
 1179.13  679.01 1179.16  679.48 1179.19  680.01  1179.2  680.13 1179.26  681.01
  1341.8  681.01  1400.3  680.26 1415.63  680.01 1640.46  680.01 1721.52  679.26
 1740.93  679.01 1954.82  679.01
BR U #Mann= 3
       0     .12  964.81    .038 1107.96     .06
BR U Banks=965.35,1110.53
BR D #Sta/Elev= 182
       0  681.01 5608.61  681.01    6426  681.01 6426.03  680.46 6426.05  680.01
 6426.08   679.5  6426.1  679.01 6426.13  678.48 6426.15  678.01 6426.18  677.48
  6426.2  677.01 6426.39  676.92 6428.31  676.01  6430.1  675.15 6430.37  675.01
 6430.72  674.84 6432.43  674.01 6432.92  673.77 6434.48  673.01 6435.16  672.68
 6436.54  672.01 6437.44  671.57 6438.59  671.01  6439.8  670.43 6440.65  670.01
 6442.28  669.22 6442.71  669.01 6444.24  668.27 6444.76  668.01 6446.58  667.13
 6446.82  667.01 6446.95  666.95 6448.86  666.01 6450.42  665.25 6450.91  665.01
 6452.13  664.42 6452.96  664.01 6454.43  663.93  6455.1  663.89 6460.27   663.6
  6462.1   663.5 6470.81  663.01 6471.35  662.62  6471.9  662.23  6472.2  662.01
 6472.42   661.9 6474.08  661.01  6475.7  660.15 6475.96  660.01  6476.6  659.67
 6477.84  659.01 6479.57   658.1 6479.72  658.01 6480.37  657.67 6481.61  657.01
 6481.74  656.94 6481.86  656.88  6482.3  656.65 6483.49  656.01 6483.71   655.9
 6484.04  655.73 6484.81  655.32  6485.4  655.01 6485.58  654.92  6487.3  654.01
 6487.67  653.82 6488.64  653.31 6489.21  653.01 6489.94  652.63 6491.12  652.01
 6491.31  651.91 6491.86  651.62 6492.77  651.15 6493.03  651.01 6494.06  650.94
 6503.84  650.31 6506.26  650.16 6507.05  650.11 6508.75  650.01 6508.85  650.01
 6513.83  649.84 6526.89   649.4 6537.17  649.01 6560.43  649.01 6561.59  649.08
 6561.97   649.1 6562.78  649.14 6562.92  649.15 6564.36  649.22 6565.82   649.3
  6566.3  649.32 6567.77   649.4 6568.66  649.45 6573.96  649.72 6574.19  649.74
 6580.29  650.01 6580.38  650.01    6582  650.21 6585.64  650.75 6586.35  650.84
 6586.59  650.88 6587.48  651.01 6589.25  651.68 6590.13  652.01 6591.74  652.62
 6592.78  653.01 6594.73  653.75 6595.43  654.01 6597.27  654.71 6598.08  655.01
  6599.8  655.66 6600.73  656.01 6603.15  656.93 6603.38  657.01 6603.58  657.09
  6604.5  657.44 6605.79  657.92 6606.02  658.01    6608  658.76 6608.67  659.01
 6610.19  659.59 6611.32  660.01 6612.33   660.4 6613.96  661.01 6616.53  661.98
 6616.61  662.01 6619.34  662.77 6620.06  662.97 6620.23  663.01  6620.8   663.1
 6621.32  663.19 6623.15  663.47 6626.64  664.01 6628.67  664.33 6633.08  665.01
 6635.74  665.43 6637.76  665.74 6639.54  666.01 6640.92  666.01 6653.36  666.53
 6654.57   666.6 6655.35  666.62 6655.93  666.65 6656.67  666.69 6657.16  666.71
 6658.27  666.77 6658.55  666.78 6662.86  667.01 6663.69  667.41 6664.93  668.01
 6665.88  668.48 6666.99  669.01 6668.15  669.57 6669.06  670.01 6670.98  670.95
 6671.12  671.01 6671.63  671.26 6673.17  672.01  6673.6  672.22 6675.22  673.01
 6677.23  673.99 6677.27  674.01 6679.04  674.88 6679.32  675.01 6679.61  675.16
 6681.37  676.01 6683.67  676.64 6685.01  677.01 6685.07  678.01 6685.11  678.58
 6685.13  679.01 6685.16  679.48 6685.19  680.01  6685.2  680.13 6685.26  681.01
  6847.8  681.01  6906.3  680.26 6921.63  680.01 7146.46  680.01 7227.52  679.26
 7246.93  679.01 7460.82  679.01
BR D #Mann= 3
       0     .12 6470.81    .038 6613.96     .06
BR D Banks=6471.35,6616.53
BC Design=,, 0 ,, 0 ,,,,,,
BC Use User HTab Curves=0
BC User HTab FreeFlow(D)= 0

Type RM Length L Ch R = 1 ,64750.50,614.08,551.53,766.27
BEGIN DESCRIPTION:
XS AG - Channel Surveyed 2017.  Overbanks from Effective FIS Model.
END DESCRIPTION:
XS GIS Cut Line= 5
2201001.15370916245794.0711192492207119.95151061246607.901368707
2207692.64687136246788.7525352542208606.94999112 247964.28511779
2208506.47712083248165.230858415
#Sta/Elev= 30
       0  692.39  173.96  690.44  203.96  683.31  428.91   677.9 1289.73   675.1
 1481.69  670.19 2684.42  674.75 3926.12  675.26 4127.07  671.51 4765.97  678.15
 5131.91  672.99 5764.81  675.72 5890.79  671.55 5992.77  674.53 6058.76  685.02
 6199.63  677.67 6259.39   681.8 6283.29  676.99  6402.8  673.226486.633   661.2
6514.983  651.016555.093  647.016609.843  649.016626.983  660.016637.133  667.01
 7045.98  660.39 7849.06  663.29 8151.71  677.51 8265.57  693.57 8487.21  709.58
#Mann= 4 ,-1 , 0
       0     .08       0 6058.76     .05       06486.633    .038       0
6626.983     .05       0
Levee=-1,6058.63,685.07,0,,,Levee 1,
#XS Ineff= 2 , 0
       06323.045   681.2  6787.9       0   681.2
Permanent Ineff=
       F       F
#Block Obstruct= 2 ,-1
 6807.82 7218.24  664.06 7485.34 7726.38  664.67
Bank Sta=6486.633,6626.983
XS Rating Curve= 0 ,0
Exp/Cntr=0.5,0.3

Type RM Length L Ch R = 1 ,64198.97,566.91,664.6,545.68
BEGIN DESCRIPTION:
Channel Surveyed 2017.  Overbanks from LiDAR.
END DESCRIPTION:
XS GIS Cut Line= 4
2201415.13609581246601.2365178912207083.13985163 247209.12998715
 2207707.9699668247330.7199670672208302.98321247248285.264317811
#Sta/Elev= 30
       0  691.02  241.34  682.79  730.41  680.84  928.92   675.1 1202.81  678.23
 1826.75  671.33 3912.86  675.55 4556.87  669.32 5506.81   674.3 5564.84  673.39
 5594.83  664.68 5656.94   663.9 5696.06  668.41  5743.2  681.93 5793.95  665.17
5967.389  661.015976.749  655.525988.379  649.016029.769  647.016097.349  650.01
6132.689  658.01 6169.46  666.33 6553.89  660.55 6667.45  665.96 6686.17   665.9
 6689.76  662.13  6806.7  669.42 7062.15  665.27 7200.52  673.35 7461.87  702.65
#Mann= 4 ,-1 , 0
       0     .08       0 5696.06     .05       05976.749    .037       0
6132.689     .06       0
Levee=-1,5733.62,681.88,0,,,,
#XS Ineff= 2 , 0
       0  5750.5     680 6427.63       0     680
Permanent Ineff=
       F       F
#Block Obstruct= 2 ,-1
    6314    6645     664    6850    7100     666
Bank Sta=5976.749,6132.689
XS Rating Curve= 0 ,0
Exp/Cntr=0.3,0.1

--- SouthChickamauga.g10 (geometry) ---

Geom Title=Proposed
Program Version=5.03

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
River Reach=Chickamauga     ,1

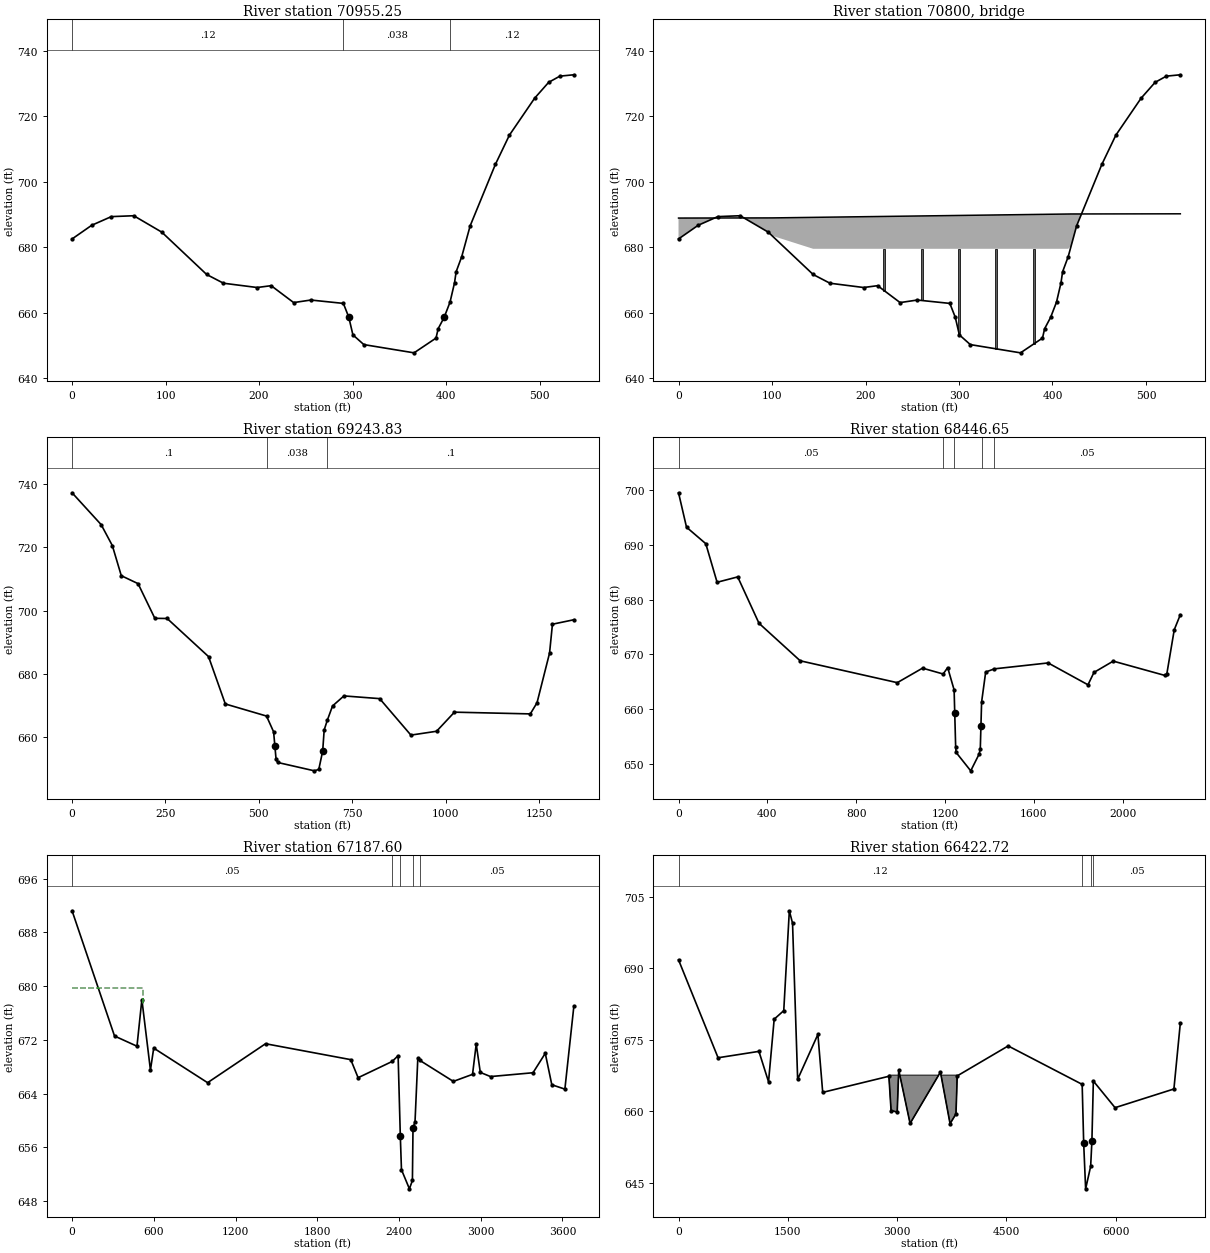
Type RM Length L Ch R = 1 ,70955.25,275.83,300.16,327.8
XS GIS Cut Line= 4
 2212515.1091626247343.6296603832212345.56119394247500.461531371
2212209.92281908247631.8612070682212125.14883472247712.396492168
#Sta/Elev= 30
       0  682.51      21  686.69   41.99  689.34   65.99  689.61   95.98  684.59
  143.98  671.64  161.97  668.97  197.97  667.66  212.96  668.22     237  663.05
   255.4  663.83   290.2   662.8     296 658.572   300.4  653.17   312.1   650.2
   365.8  647.68   389.3  652.19   391.6  655.07     398 658.528   404.3   663.2
   409.1  669.11  410.82  672.48  416.81   677.1   425.8  686.51  452.79  705.31
  467.78  714.25  494.76  725.55  509.75   730.4  521.75   732.3  536.74  732.72
#Mann= 3 ,-1 , 0
       0     .12       0   290.2    .038       0   404.3     .12       0
Bank Sta=296,398
XS Rating Curve= 0 ,0
Exp/Cntr=0.5,0.3

Type RM Length L Ch R = 3 ,70800   ,,,
BEGIN DESCRIPTION:
Louisville and Nashville Railroad
END DESCRIPTION:
Bridge Culvert--1,0,-1,-1, 0
Deck Dist Width WeirC Skew NumUp NumDn MinLoCord MaxHiCord MaxSubmerge Is_Ogee
150,18,2.6,0, 6, 6, , , 0.98, 0, 0,0,,
       0     100     100     420     420  536.74
   688.9  688.95  688.95  690.15  690.15   690.2
     600     600   679.5   679.5     600     600
       0     300     300     620     620 1023.46
  688.75  688.95  688.95  690.15  690.15  690.55
     600     600   679.5   679.5     600     600
Pier Skew, UpSta & Num, DnSta & Num=  ,220, 2 ,420, 2 , 0 , 0 , 0 ,,
       2       2
     600   679.5
       2       2
     600   679.5
Pier Skew, UpSta & Num, DnSta & Num=  ,260, 2 ,460, 2 , 0 , 0 , 0 ,,
       2       2
     600   679.5
       2       2
     600   679.5
Pier Skew, UpSta & Num, DnSta & Num=  ,300, 2 ,500, 2 , 0 , 0 , 0 ,,
       2       2
     600   679.5
       2       2
     600   679.5
Pier Skew, UpSta & Num, DnSta & Num=  ,340, 2 ,540, 2 , 0 , 0 , 0 ,,
       2       2
     600   679.5
       2       2
     600   679.5
Pier Skew, UpSta & Num, DnSta & Num=  ,380, 2 ,580, 2 , 0 , 0 , 0 ,,
       2       2
     600   679.5
       2       2
     600   679.5
BR Coef=-1 , 0 , 0 ,, 0 ,,,0.8,-1,1.2,1,
WSPro=,,,, 1 ,,,, 0 ,,,, 0 ,,,,-1 ,-1 ,-1 , 0 , 0 , 0 , 0 , 0
BC Design=,, 0 ,, 0 ,,,,,,
BC Use User HTab Curves=0
BC User HTab FreeFlow(D)= 0

Type RM Length L Ch R = 1 ,69243.83,792.28,797.18,852.81
BEGIN DESCRIPTION:
Overbank geometry revised as per Preliminary Plans.
END DESCRIPTION:
XS GIS Cut Line= 4
2211207.94142106246352.9514603322210853.77455327246684.511932313
2210725.67164364 246872.898564162210567.42687286247483.271251231
#Sta/Elev= 30
       0   737.3   77.86  727.21  107.81  720.57  131.77  711.03  176.69  708.51
  221.61  697.52  254.55  697.47  365.36   685.4  410.28  670.39   520.6  666.56
   539.6  661.56     543 657.078   546.2  652.86   550.6  651.85   648.9   649.2
   660.6  649.67     671 655.457     675  662.15   683.4  665.23   697.4  669.76
   727.9  672.94  823.53  672.08  907.21  660.52  975.94  661.74 1023.75  667.79
 1226.96  667.24  1244.9  670.78 1278.42686.50521286.163 695.655 1343.51  697.07
#Mann= 3 ,-1 , 0
       0      .1       0   520.6    .038       0   683.4      .1       0
Bank Sta=543,671
XS Rating Curve= 0 ,0
Exp/Cntr=0.3,0.1

Type RM Length L Ch R = 1 ,68446.65,1284.67,1259.06,1027.68
BEGIN DESCRIPTION:
Overbank geometry revised as per Preliminary Plans.
END DESCRIPTION:
XS GIS Cut Line= 4
2211034.62571979245365.8055095822210220.79547037246232.384015962
2210070.08616489246390.6287866832209595.35185272247098.962522328
#Sta/Elev= 30
       0   699.5   35.93  693.22  122.77  690.21  173.68  683.17  266.51  684.15
  362.33  675.69  547.99  668.84  985.19  664.85 1098.98   667.5 1191.81  666.43
  1212.2   667.6  1241.2  663.53    1244  659.33  1248.1  653.18  1250.2  652.12
    1316  648.76    1354  651.83  1359.1  652.77    1362 656.973    1365  661.32
  1383.4  666.79 1422.31  667.37 1664.65  668.45 1844.17  664.46  1871.1  666.72
 1957.86  668.78 2191.23  666.162199.101666.41192232.703 674.5072260.045 677.248
#Mann= 5 ,-1 , 0
       0     .05       0 1191.81     .12       0  1241.2    .038       0
    1365     .12       0 1422.31     .05       0
Bank Sta=1244,1362
XS Rating Curve= 0 ,0
Exp/Cntr=0.3,0.1

Type RM Length L Ch R = 1 ,67187.60,1141.18,764.88,504.07
BEGIN DESCRIPTION:
Overbank geometry revised as per Preliminary Plans.
END DESCRIPTION:
XS GIS Cut Line= 5
2211087.37397669244348.517697766 2209866.6286025244770.503753066
2209150.75940165245531.5857456032209060.33381833 245735.04330796
2208864.41172126246842.756703034
#Sta/Elev= 30
       0  691.22  311.67  672.57  476.49  671.05  512.45     678  575.39   667.5
  599.36  670.77  994.94  665.62 1420.37  671.42 2046.09  669.05 2099.98  666.36
    2350  668.78  2393.7  669.64    2410 657.618  2418.3  652.66  2476.7  649.81
  2498.7  651.06    2503 658.864  2517.9  659.83 2538.37  669.27 2553.22  668.94
 2799.13  665.81 2940.12  666.86 2967.12  671.37 2997.12  667.15 3072.11  666.53
 3384.09   667.1 3474.08  669.99 3522.08  665.31 3618.07  664.66 3683.97  677.01
#Mann= 5 ,-1 , 0
       0     .05       0    2350     .12       0    2410    .038       0
    2503     .12       0 2553.22     .05       0
#XS Ineff= 2 , 0
          517.83  679.79
Permanent Ineff=
       F       F
Bank Sta=2410,2503
XS Rating Curve= 0 ,0
Exp/Cntr=0.3,0.1

Type RM Length L Ch R = 1 ,66422.72,600.54,741.47,320.15
BEGIN DESCRIPTION:
Overbank geometry revised as per Preliminary Plans.
END DESCRIPTION:
XS GIS Cut Line= 4
2204859.31192881241091.9407891042208355.76781535245321.848628834
2208375.86238943245522.7943694592208466.28797269246718.421526045
#Sta/Elev= 30
       0  691.76   542.8  671.23 1103.58  672.57 1235.53  666.191312.918679.3181
1444.479 681.1111521.042 702.0551565.081 699.4531635.164 666.707 1913.28  676.13
 1979.26  663.97 2887.89  667.35 2917.88  660.16 3001.85  659.84 3022.84  668.66
 3178.77  657.45  3595.6  668.23 3727.55   657.4 3808.52  659.45 3826.51  667.43
 4525.26  673.71  5541.1  665.65    5562  653.29  5588.7  643.74  5657.7  648.47
 5674.78 653.768  5694.6  666.35 5992.64  660.766800.579664.68236888.678 678.507
#Mann= 4 ,-1 , 0
       0     .12       0  5541.1    .038       0  5657.7     .12       0
  5694.6     .05       0
#XS Ineff= 2 , 0
         1428.67  680.65
Permanent Ineff=
       F       F
#Block Obstruct= 1 ,-1
  2889.7 3819.02  667.59
Bank Sta=5562,5674.78
XS Rating Curve= 0 ,0
Exp/Cntr=0.3,0.1

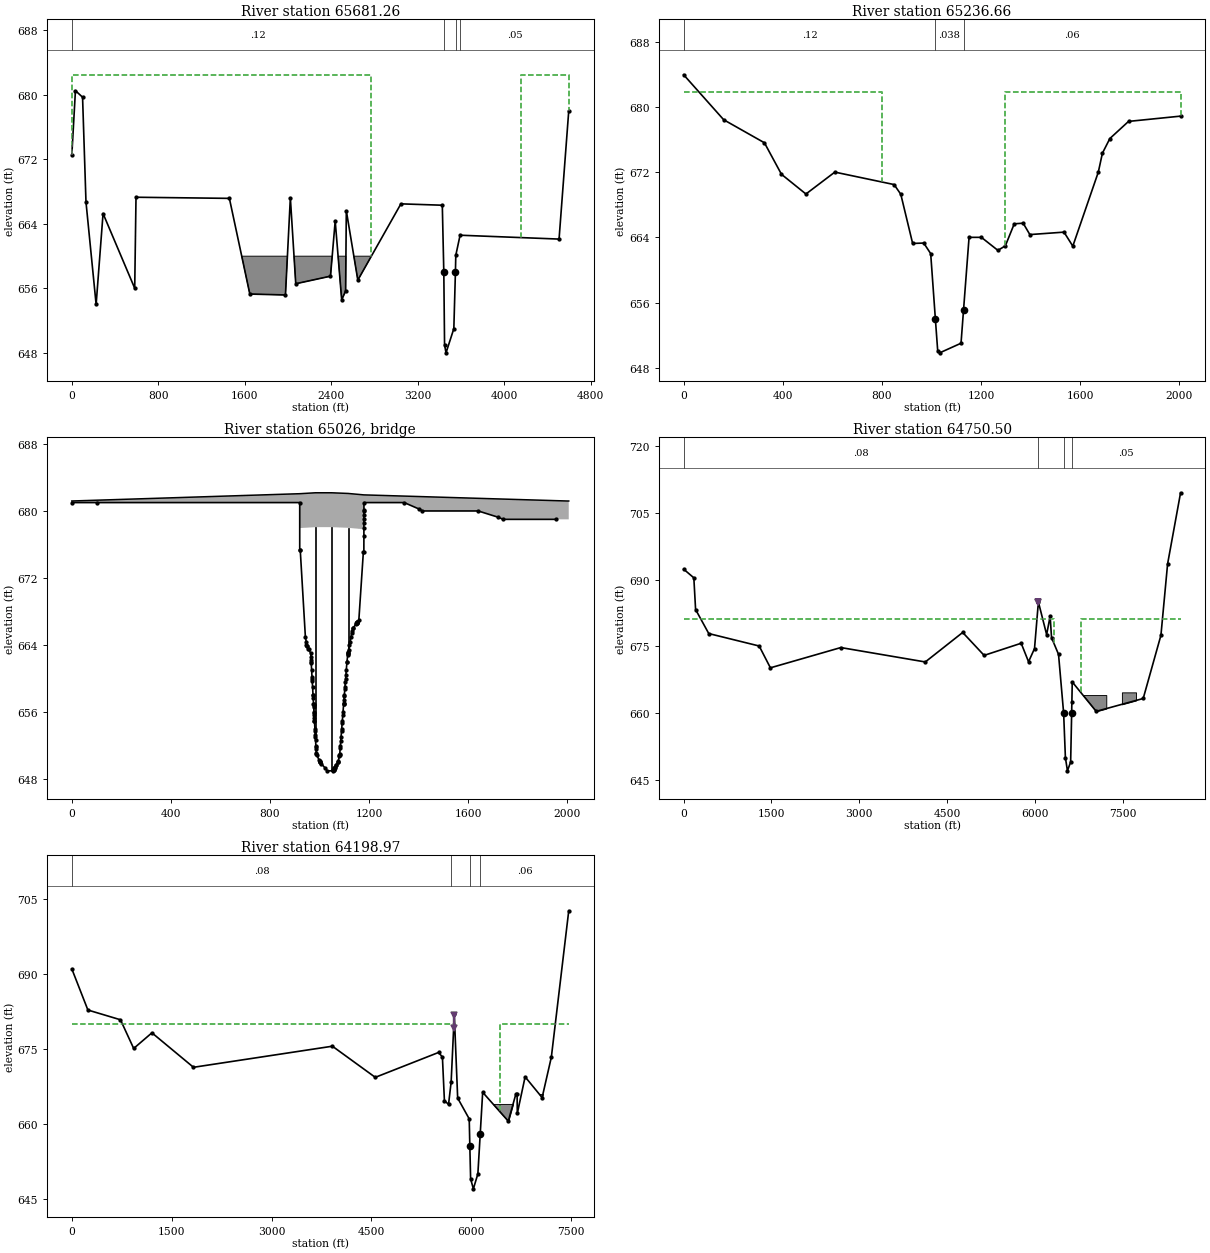
Type RM Length L Ch R = 1 ,65681.26,988.49,444.59,268.93
BEGIN DESCRIPTION:
Channel Surveyed 2017.  Overbanks from LiDAR.  Overbank geometry revised as per Preliminary Plans.
END DESCRIPTION:
XS GIS Cut Line= 3
2204851.12036556243919.1549398152208115.16895555246078.658494815
2208430.47180264 246685.43812114
#Sta/Elev= 30
       0  672.56   33.38  680.53   99.37  679.72  130.98  666.72  224.86  654.01
  288.95  665.29  581.86  656.02  593.84  667.31 1457.77  667.17 1646.92   655.3
 1976.57  655.19  2021.9  667.25 2071.78  656.58  2393.2  657.52 2436.77  664.36
 2496.74  654.59 2533.19  655.67 2539.64  665.64 2646.12  657.03 3044.76  666.49
 3427.76  666.32 3441.68  658.01 3448.63  649.01  3462.1  648.01 3534.42  651.01
 3549.08  658.01 3552.59  660.11 3592.23   662.6 4508.01  662.12 4597.56678.0232
#Mann= 4 ,-1 , 0
       0     .12       0 3441.68    .038       0 3552.59     .12       0
 3592.23     .05       0
#XS Ineff= 2 , 0
       0 2766.25   682.5 4153.63       0   682.5
Permanent Ineff=
       F       F
#Block Obstruct= 1 ,-1
    1500    3000     660
Bank Sta=3441.68,3549.08
XS Rating Curve= 0 ,0
Exp/Cntr=0.3,0.1

Type RM Length L Ch R = 1 ,65236.66,494.09,486.16,508.59
BEGIN DESCRIPTION:
XS AH - Surveyed Section 2017.  Overbank geometry revised as per Preliminary Plans.
END DESCRIPTION:
XS GIS Cut Line= 4
2206587.44529802245884.4967025222207481.65384372246226.104461551
2207672.55229728246276.3408967262208406.00425053246708.374239028
#Sta/Elev= 30
       0  683.97  161.53  678.45  326.06  675.62  394.86  671.75  493.58  669.33
  610.24  672.02  849.55  670.49  876.47   669.3  924.34  663.26   969.2  663.31
  997.18  662.01 1016.02  654.01 1025.66  650.01 1033.58  649.83 1119.63  651.01
 1129.66  655.05 1152.09  664.01 1201.82  664.01 1268.54  662.41 1298.51  662.97
 1334.48  665.67 1370.44  665.75 1397.42  664.35  1535.3  664.651570.877662.9298
1673.794672.01771690.303 674.3391720.439676.14351795.815678.24552005.833 678.893
#Mann= 3 , 0 , 0
       0     .12       0 1016.02    .038       0 1129.66     .06       0
#XS Ineff= 2 , 0
       0  800.37  681.91 1298.57       0  681.91
Permanent Ineff=
       F       F
Bank Sta=1016.02,1129.66
XS Rating Curve= 0 ,0
Exp/Cntr=0.5,0.3

Type RM Length L Ch R = 3 ,65026   ,,,
BEGIN DESCRIPTION:
Proposed (Preliminary) Interstate 75 Bridge
END DESCRIPTION:
Bridge Culvert--1,0,-1,-1, 0
Deck Dist Width WeirC Skew NumUp NumDn MinLoCord MaxHiCord MaxSubmerge Is_Ogee
119.63,179.25,2.6,0, 10, 9, , , 0.98, 0, 2,4,,
       0     920     920  983.37 1049.27 1115.48 1178.94 1178.94 1999.88    2006
   681.2  682.07  682.07  682.18  682.18   682.1  681.93  681.93   681.2   681.2
     600     600  677.97  678.08  678.08     678  677.83     600     600     600
       0    6426    6426 6489.37 6555.27 6621.48 6684.94 6684.94 8487.21
   681.2  682.07  682.07  682.18  682.18   682.1  681.93  681.93   681.2
     600     600  677.97  678.08  678.08     678  677.83     600     600
Pier Skew, UpSta & Num, DnSta & Num=  ,983.37, 2 ,6489.37, 2 , 0 , 0 , 0 ,,
       3       3
     600   678.7
       3       3
     600   678.7
Pier Skew, UpSta & Num, DnSta & Num=  ,1049.27, 2 ,6555.27, 2 , 0 , 0 , 0 ,,
       3       3
     600   678.7
       3       3
     600   678.7
Pier Skew, UpSta & Num, DnSta & Num=  ,1115.48, 2 ,6621.48, 2 , 0 , 0 , 0 ,,
       3       3
     600   678.7
       3       3
     600   678.7
Abutment Skew #Up #Dn= , 3 , 3
     920   922.2  942.82
  675.31  675.31     665
    6426  6428.2 6448.82
  675.31  675.31     665
Abutment Skew #Up #Dn= , 3 , 3
 1158.63 1177.01 1178.94
  666.98  675.17  675.17
 6664.63 6683.01 6684.94
  666.98  675.17  675.17
BR Coef=-1 , 1 , 1 ,1.25, 0 ,,,0.8,0,2,0,
WSPro=,,,, 1 ,,,, 0 ,,,, 0 ,,,,-1 ,-1 ,-1 , 0 , 0 , 0 , 0 , 0
BR U #Sta/Elev= 136
       0  681.01  102.61  681.01     920  681.01     920  675.31   922.2  675.31
  942.82     665  946.13  664.42  946.96  664.01  948.43  663.93   949.1  663.89
  954.27   663.6   956.1   663.5  964.81  663.01  965.35  662.62   965.9  662.23
   966.2  662.01  966.42   661.9  968.08  661.01   969.7  660.15  969.96  660.01
   970.6  659.67  971.84  659.01  973.57   658.1  973.72  658.01  974.37  657.67
  975.61  657.01  975.74  656.94  975.86  656.88   976.3  656.65  977.49  656.01
  977.71   655.9  978.04  655.73  978.81  655.32   979.4  655.01  979.58  654.92
   981.3  654.01  981.67  653.82  982.64  653.31  983.21  653.01  983.94  652.63
  985.12  652.01  985.31  651.91  985.86  651.62  986.77  651.15  987.03  651.01
  988.06  650.94  997.84  650.31 1000.26  650.16 1001.05  650.11 1002.75  650.01
 1002.85  650.01 1007.83  649.84 1020.89   649.4 1031.17  649.01 1054.43  649.01
 1055.59  649.08 1055.97   649.1 1056.78  649.14 1056.92  649.15 1058.36  649.22
 1059.82   649.3  1060.3  649.32 1061.77   649.4 1062.66  649.45 1067.96  649.72
 1068.19  649.74 1074.29  650.01 1074.38  650.01    1076  650.21 1079.64  650.75
 1080.35  650.84 1080.59  650.88 1081.48  651.01 1083.25  651.68 1084.13  652.01
 1085.74  652.62 1086.78  653.01 1088.73  653.75 1089.43  654.01 1091.27  654.71
 1092.08  655.01  1093.8  655.66 1094.73  656.01 1097.15  656.93 1097.38  657.01
 1097.58  657.09  1098.5  657.44 1099.79  657.92 1100.02  658.01    1102  658.76
 1102.67  659.01 1104.19  659.59 1105.32  660.01 1106.33   660.4 1107.96  661.01
 1110.53  661.98 1110.61  662.01 1113.34  662.77 1114.06  662.97 1114.23  663.01
  1114.8   663.1 1115.32  663.19 1117.15  663.47 1120.64  664.01 1122.67  664.33
 1127.08  665.01 1129.74  665.43 1131.76  665.74 1133.54  666.01 1134.92  666.01
 1147.36  666.53 1148.57   666.6 1149.35  666.62 1149.93  666.65 1150.67  666.69
 1151.16  666.71 1152.27  666.77 1152.55  666.78 1158.63  666.98 1177.01  675.17
 1178.94  675.17 1179.01  677.01 1179.07  678.01 1179.11  678.58 1179.13  679.01
 1179.16  679.48 1179.19  680.01  1179.2  680.13 1179.26  681.01  1341.8  681.01
  1400.3  680.26 1415.63  680.01 1640.46  680.01 1721.52  679.26 1740.93  679.01
 1954.82  679.01
BR U #Mann= 3
       0     .12  965.35    .038 1110.53     .06
BR U Banks=965.35,1110.53
BR D #Sta/Elev= 136
    5506  681.01 5608.61  681.01    6426  681.01    6426  675.31  6428.2  675.31
 6448.82     665 6452.13  664.42 6452.96  664.01 6454.43  663.93  6455.1  663.89
 6460.27   663.6  6462.1   663.5 6470.81  663.01 6471.35  662.62  6471.9  662.23
  6472.2  662.01 6472.42   661.9 6474.08  661.01  6475.7  660.15 6475.96  660.01
  6476.6  659.67 6477.84  659.01 6479.57   658.1 6479.72  658.01 6480.37  657.67
 6481.61  657.01 6481.74  656.94 6481.86  656.88  6482.3  656.65 6483.49  656.01
 6483.71   655.9 6484.04  655.73 6484.81  655.32  6485.4  655.01 6485.58  654.92
  6487.3  654.01 6487.67  653.82 6488.64  653.31 6489.21  653.01 6489.94  652.63
 6491.12  652.01 6491.31  651.91 6491.86  651.62 6492.77  651.15 6493.03  651.01
 6494.06  650.94 6503.84  650.31 6506.26  650.16 6507.05  650.11 6508.75  650.01
 6508.85  650.01 6513.83  649.84 6526.89   649.4 6537.17  649.01 6560.43  649.01
 6561.59  649.08 6561.97   649.1 6562.78  649.14 6562.92  649.15 6564.36  649.22
 6565.82   649.3  6566.3  649.32 6567.77   649.4 6568.66  649.45 6573.96  649.72
 6574.19  649.74 6580.29  650.01 6580.38  650.01    6582  650.21 6585.64  650.75
 6586.35  650.84 6586.59  650.88 6587.48  651.01 6589.25  651.68 6590.13  652.01
 6591.74  652.62 6592.78  653.01 6594.73  653.75 6595.43  654.01 6597.27  654.71
 6598.08  655.01  6599.8  655.66 6600.73  656.01 6603.15  656.93 6603.38  657.01
 6603.58  657.09  6604.5  657.44 6605.79  657.92 6606.02  658.01    6608  658.76
 6608.67  659.01 6610.19  659.59 6611.32  660.01 6612.33   660.4 6613.96  661.01
 6616.53  661.98 6616.61  662.01 6619.34  662.77 6620.06  662.97 6620.23  663.01
  6620.8   663.1 6621.32  663.19 6623.15  663.47 6626.64  664.01 6628.67  664.33
 6633.08  665.01 6635.74  665.43 6637.76  665.74 6639.54  666.01 6640.92  666.01
 6653.36  666.53 6654.57   666.6 6655.35  666.62 6655.93  666.65 6656.67  666.69
 6657.16  666.71 6658.27  666.77 6658.55  666.78 6664.63  666.98 6683.01  675.17
 6684.94  675.17 6685.01  677.01 6685.07  678.01 6685.11  678.58 6685.13  679.01
 6685.16  679.48 6685.19  680.01  6685.2  680.13 6685.26  681.01  6847.8  681.01
  6906.3  680.26 6921.63  680.01 7146.46  680.01 7227.52  679.26 7246.93  679.01
 7460.82  679.01
BR D #Mann= 3
    5506     .12 6471.35    .038 6616.53     .06
BR D Banks=6471.35,6616.53
BC Design=,, 0 ,, 0 ,,,,,,
BC Use User HTab Curves=0
BC User HTab FreeFlow(D)= 0

Type RM Length L Ch R = 1 ,64750.50,614.08,551.53,766.27
BEGIN DESCRIPTION:
XS AG - Channel Surveyed 2017.  Overbanks from Effective FIS Model.
END DESCRIPTION:
XS GIS Cut Line= 5
2201001.15370916245794.0711192492207119.95151061246607.901368707
2207692.64687136246788.7525352542208606.94999112 247964.28511779
2208506.47712083248165.230858415
#Sta/Elev= 30
       0  692.39  173.96  690.44  203.96  683.31  428.91   677.9 1289.73   675.1
 1481.69  670.19 2684.42  674.75 4127.07  671.51 4765.97  678.15 5131.91  672.99
 5764.81  675.72 5890.79  671.55 5992.77  674.53 6058.76  685.02 6199.63  677.67
 6259.39   681.8 6283.29  676.99  6402.8  673.226489.963  660.016520.133  649.98
6555.093  647.016609.843  649.016626.983  660.016630.683  662.426637.133  667.01
 7045.98  660.39 7849.06  663.29 8151.71  677.51 8265.57  693.57 8487.21  709.58
#Mann= 4 ,-1 , 0
       0     .08       0 6058.76     .05       06489.963    .038       0
6630.683     .05       0
Levee=-1,6058.63,685.07,0,,,Levee 1,
#XS Ineff= 2 , 0
       0 6332.36   681.2 6778.58       0   681.2
Permanent Ineff=
       F       F
#Block Obstruct= 2 ,-1
 6807.82 7218.24  664.06 7485.34 7726.38  664.67
Bank Sta=6489.963,6626.983
XS Rating Curve= 0 ,0
Exp/Cntr=0.5,0.3

Type RM Length L Ch R = 1 ,64198.97,566.91,664.6,545.68
BEGIN DESCRIPTION:
Channel Surveyed 2017.  Overbanks from LiDAR.
END DESCRIPTION:
XS GIS Cut Line= 4
2201415.13609581246601.2365178912207083.13985163 247209.12998715
 2207707.9699668247330.7199670672208302.98321247248285.264317811
#Sta/Elev= 30
       0  691.02  241.34  682.79  730.41  680.84  928.92   675.1 1202.81  678.23
 1826.75  671.33 3912.86  675.55 4556.87  669.32 5506.81   674.3 5564.84  673.39
 5594.83  664.68 5656.94   663.9 5696.06  668.41  5743.2  681.93 5793.95  665.17
5967.389  661.015976.749  655.525988.379  649.016029.769  647.016097.349  650.01
6132.689  658.01 6169.46  666.33 6553.89  660.55 6667.45  665.96 6686.17   665.9
 6689.76  662.13  6806.7  669.42 7062.15  665.27 7200.52  673.35 7461.87  702.65
#Mann= 4 ,-1 , 0
       0     .08       0 5696.06     .05       05976.749    .037       0
6132.689     .06       0
Levee=-1,5733.62,681.88,0,,,,
#XS Ineff= 2 , 0
       0  5750.5     680 6422.97       0     680
Permanent Ineff=
       F       F
#Block Obstruct= 2 ,-1
    6314    6645     664    6850    7100     666
Bank Sta=5976.749,6132.689
XS Rating Curve= 0 ,0
Exp/Cntr=0.3,0.1